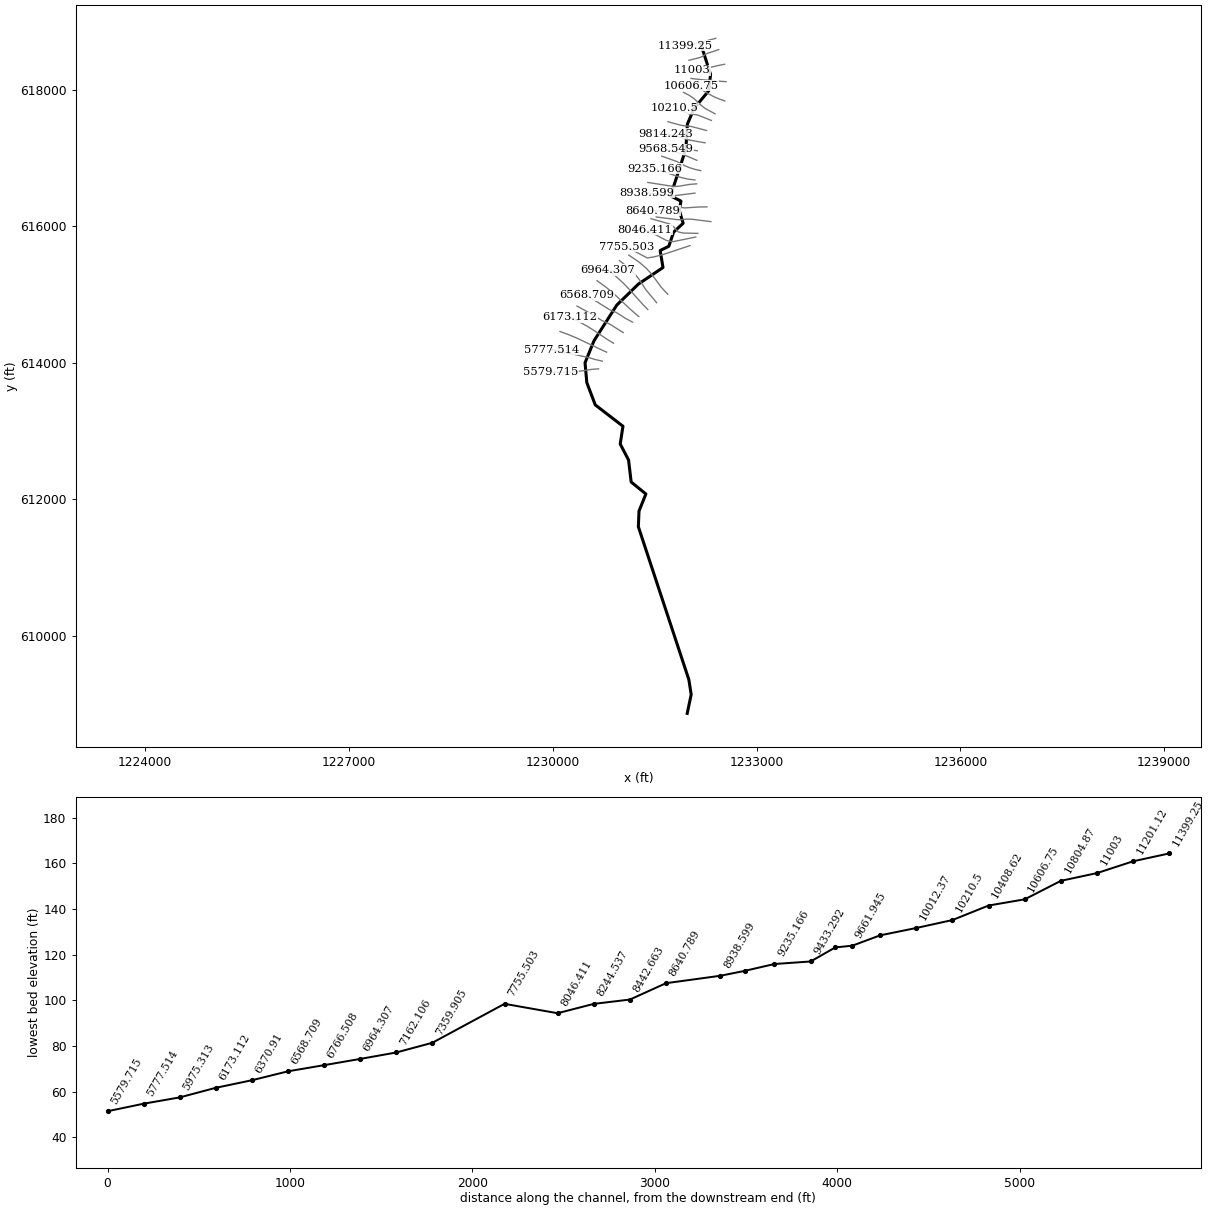
--- 301_ras.prj (project) ---

Proj Title=301
Current Plan=p01
Default Exp/Contr=0.3,0.1
English Units
Geom File=g01
Flow File=f01
Plan File=p01
Y Axis Title=Elevation
X Axis Title(PF)=Main Channel Distance
X Axis Title(XS)=Station
BEGIN DESCRIPTION:
RFD model 301 exported to HEC-RAS
END DESCRIPTION:

--- 301_ras.p01 (plan) ---

Plan Title=Plan 01
Program Version=4.10
Short Identifier=Plan 01
Geom File=g01
Flow File=f01
Subcritical Flow
Calc Critical at every XS
Secant Critical Depth

--- 301_ras.f01 (steady flow) ---

Flow Title=Flow 01
Program Version=5.01
Number of Profiles= 5
Profile Names=10yr,25yr,50yr,100yr,500yr
River Rch & RM=301,57,11399.25
  422.09  422.09  422.09  660.47  788.57
River Rch & RM=301,57,11201.12
  422.85  422.85  422.85  662.06  790.73
River Rch & RM=301,57,   11003
  433.32  433.32  433.32  683.91  820.63
River Rch & RM=301,57,10804.87
  462.62  462.62  462.62  745.96  906.26
River Rch & RM=301,57,10606.75
  484.41  484.41  484.41  792.95  971.79
River Rch & RM=301,57,10408.62
  498.93  498.93  498.93  824.64 1016.32
River Rch & RM=301,57, 10210.5
  503.63  503.63  503.63  834.96 1030.87
River Rch & RM=301,57,10012.37
  513.96  513.96  513.96  857.78 1063.12
River Rch & RM=301,57,9814.243
  522.89  522.89  522.89   877.6 1091.25
River Rch & RM=301,57,9661.945
  525.08  525.08  525.08  882.49 1098.21
River Rch & RM=301,57,9568.549
  526.72  526.72  526.72  886.15 1103.41
River Rch & RM=301,57,9433.292
  536.91  536.91  536.91  908.98 1135.95
River Rch & RM=301,57,9235.166
  539.02  539.02  539.02  913.72 1142.73
River Rch & RM=301,57,9071.935
  624.91  624.91  624.91 1111.85 1430.08
River Rch & RM=301,57,8938.599
  626.17  626.17  626.17 1114.81 1434.44
River Rch & RM=301,57,8640.789
  687.11  687.11  687.11 1261.05 1651.45
River Rch & RM=301,57,8442.663
  688.91  688.91  688.91 1265.46 1658.04
River Rch & RM=301,57,8244.537
  697.84  697.84  697.84 1287.27 1690.75
River Rch & RM=301,57,8046.411
  702.42  702.42  702.42 1298.48 1707.59
River Rch & RM=301,57,7755.503
  747.13  747.13  747.13 1409.32 1875.17
River Rch & RM=301,57,7359.905
   759.4   759.4   759.4 1440.12 1922.08
River Rch & RM=301,57,7162.106
  764.04  764.04  764.04  1451.8 1939.92
River Rch & RM=301,57,6964.307
  770.16  770.16  770.16 1467.25 1963.53
River Rch & RM=301,57,6766.508
  774.09  774.09  774.09 1477.22 1978.78
River Rch & RM=301,57,6568.709
   779.2   779.2   779.2 1490.16  1998.6
River Rch & RM=301,57, 6370.91
  828.18  828.18  828.18 1615.75 2192.26
River Rch & RM=301,57,6173.112
  831.98  831.98  831.98 1625.59 2207.52
River Rch & RM=301,57,5975.313
     849     849     849 1669.87 2276.39
River Rch & RM=301,57,5777.514
  851.35  851.35  851.35 1676.01 2285.96
River Rch & RM=301,57,5579.715
  872.08  872.08  872.08  1730.4 2370.93
River Rch & RM=301,57,5381.916
  875.59  875.59  875.59 1739.64 2385.42
River Rch & RM=301,57,5184.117
  882.54  882.54  882.54    1758  2414.2
River Rch & RM=301,57,4986.318
  886.23  886.23  886.23 1767.76 2429.53
River Rch & RM=301,57,4788.519
  887.94  887.94  887.94  1772.3 2436.66
River Rch & RM=301,57,4639.002
  889.16  889.16  889.16 1775.53 2441.74
River Rch & RM=301,57,4473.021
  890.14  890.14  890.14 1778.12 2445.81
River Rch & RM=301,57,  4379.4
   898.6   898.6   898.6 1800.59 2481.17
River Rch & RM=301,57,  4103.4
  901.47  901.47  901.47 1808.23 2493.21
River Rch & RM=301,57,3912.017
  904.81  904.81  904.81 1817.12 2507.21
River Rch & RM=301,57,3720.633
  905.76  905.76  905.76 1819.65 2511.21
River Rch & RM=301,57, 3529.25
  918.43  918.43  918.43 1853.51 2564.68
River Rch & RM=301,57,3146.482
  920.74  920.74  920.74 1859.71  2574.5
River Rch & RM=301,57,2955.099
  929.92  929.92  929.92 1884.36 2613.54
River Rch & RM=301,57,2763.715
 1139.94 1139.94 1139.94  2469.1 3559.44
River Rch & RM=301,57,2572.332
 1141.94 1141.94 1141.94 2474.85  3568.9
River Rch & RM=301,57,2380.948
  1143.1  1143.1  1143.1 2478.19 3574.42
River Rch & RM=301,57,2189.565
 1196.14 1196.14 1196.14 2631.95    3829
River Rch & RM=301,57,1998.181
 1197.37 1197.37 1197.37 2635.57 3835.01
River Rch & RM=301,57,1806.797
 1236.43 1236.43 1236.43 2750.27 4026.36
River Rch & RM=301,57,1615.414
 1237.16 1237.16 1237.16 2752.44 4029.99
River Rch & RM=301,57, 1424.03
 1238.34 1238.34 1238.34 2755.91  4035.8
River Rch & RM=301,57,1232.647
 1239.51 1239.51 1239.51 2759.38  4041.6
River Rch & RM=301,57,1041.263
 1240.69 1240.69 1240.69 2762.85  4047.4
River Rch & RM=301,57,691.2999
  1247.1  1247.1  1247.1 2781.82 4079.19
River Rch & RM=301,57,345.2631
 1250.15 1250.15 1250.15 2790.84 4094.31
River Rch & RM=301,57,       0
 1279.56 1279.56 1279.56 2878.34 4241.35
Boundary for River Rch & Prof#=301,57,1
Up Type= 0
Dn Type= 2
Boundary for River Rch & Prof#=301,57,2
Up Type= 0
Dn Type= 2
Boundary for River Rch & Prof#=301,57,2
Up Type= 0
Dn Type= 2
Boundary for River Rch & Prof#=301,57,2
Up Type= 0
Dn Type= 2
Boundary for River Rch & Prof#=301,57,2
Up Type= 0
Dn Type= 2

--- 301_ras.g01 (geometry) ---

Geom Title=301
Program Version=4.10

River Reach=301,57
Reach XY= 30
1232172.86616188618693.9559084481232323.69943699618223.122710556
1232296.19943812617983.1227826331232081.19949409617725.622865319
1231982.86618307617495.6229364721231960.36617914617130.623045489
1231734.53289244616443.9565892521231887.86617836616367.289940879
1231862.86618179616232.2899817081231920.36615932616043.123369589
1231779.53286371615912.2900791471231709.53287843615705.623475879
1231582.03291425615643.1234981271231623.69956133615393.956904262
1231263.69966057615153.1236528751230943.73446825 614843.74875401
1230608.66510749614321.179474488 1230476.7802501613998.510597214
1230502.88416138613706.7609054451230627.26165199613381.229667664
1231034.86283526613068.3287705031230994.25203684612808.478947818
1231117.09400535612573.5436667651231155.48211327 612251.08348088
1231371.99108982 612076.033659981231270.64645278611824.207613856
1231261.43329799611595.414435387 1232004.4274596609355.449577704
1232038.52330369 609136.261966721231980.07326627608861.059746996

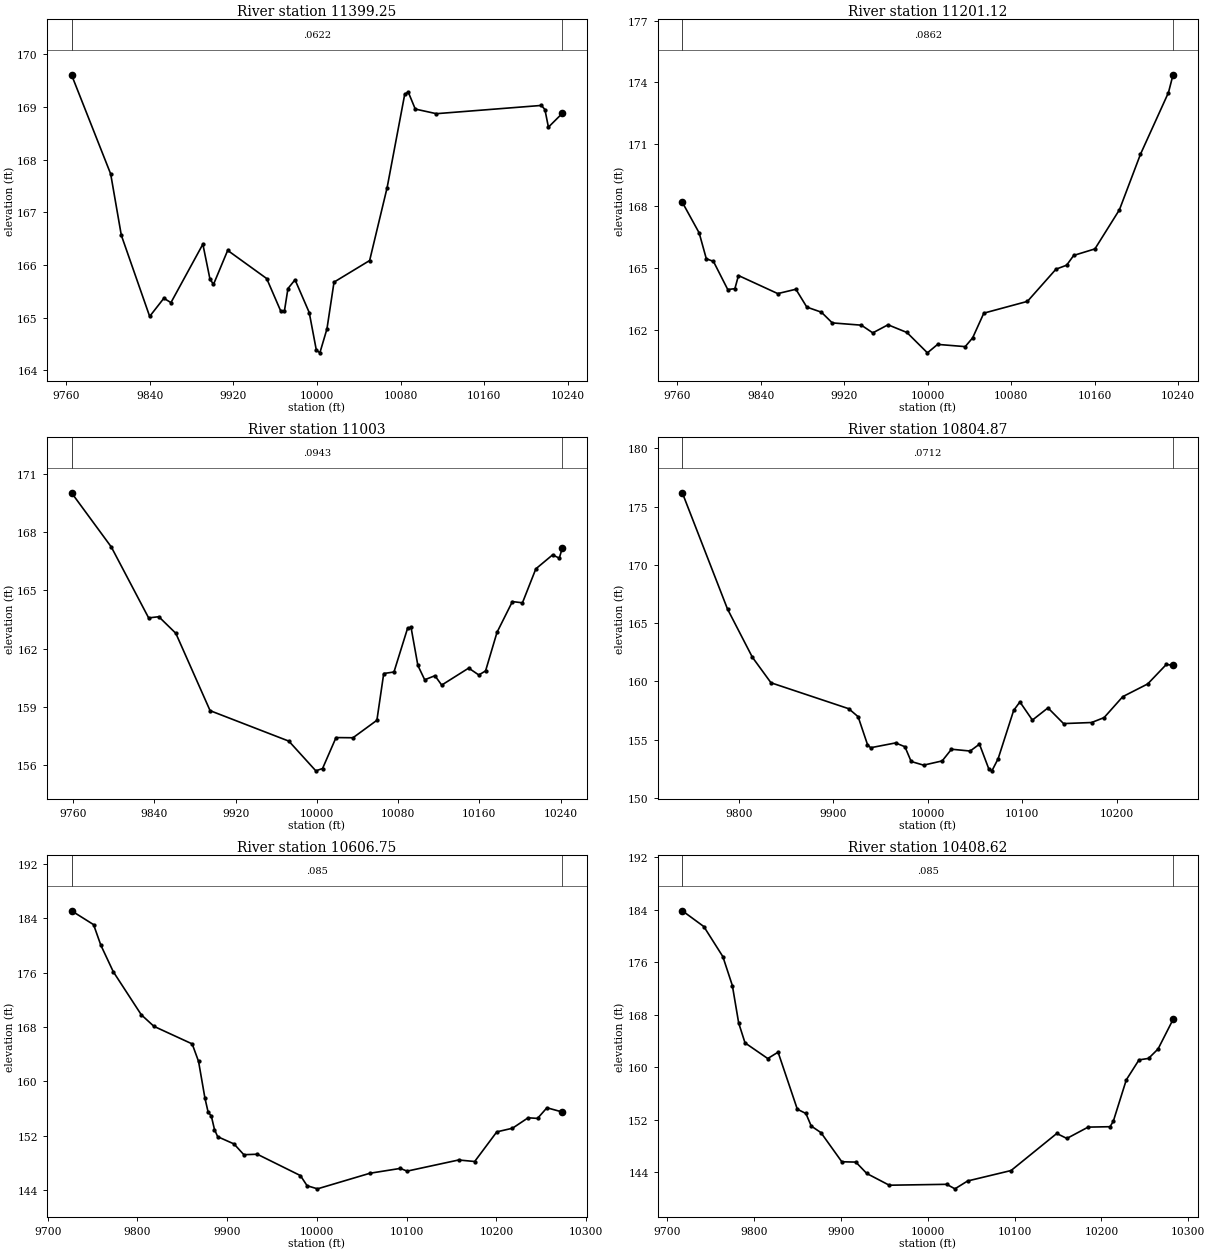
Type RM Length L Ch R = 1 ,11399.25,198.125700,198.125700,198.125700
XS GIS Cut Line= 6
1232400.16886328618752.4808748381232174.09197104 618693.25064832
1232172.16090173618692.7300992611232108.92249997618676.585939956
1232022.47554133618657.0472475541231944.11683134 618641.90625784
#Sta/Elev= 30
9765.293169.60869802.746167.72639812.921166.56349840.053165.02199853.619165.3669
9860.403165.28379890.927 166.393 9897.71165.73139901.101165.62919914.668166.2752
9951.975165.74089965.541165.11799968.933165.12349972.324165.55099979.107165.7173
9992.673165.09539999.457164.383110002.85164.330610009.62164.784110016.39165.6729
10050.45166.082710067.18167.4665   10084169.236410087.36169.282410094.09 168.958
10114.27168.870110214.78169.026810218.12168.947410221.46168.6143 10234.7168.8754
#Mann= 3 , 0 , 0
9765.293  0.0622       09765.293  0.0622       0 10234.7  0.0622       0
#XS Ineff= 2 , 0
       0                               0
Bank Sta=9765.293,10234.7
Exp/Cntr=0.3,0.1

Type RM Length L Ch R = 1 ,11201.12,198.125800,198.125800,198.125800
XS GIS Cut Line= 6
1232445.02805885618587.2020260881232282.00691892618534.283844322
1232242.65676544618515.1588116491232205.75778986618487.987641486
1232169.02530544618472.3709237971232005.28875145618430.580096996
#Sta/Elev= 30
 9764.93168.18829781.075166.70329787.922165.45059794.769165.32169808.462163.9572
9815.309163.99999818.733164.6367 9856.39163.76059873.759163.97169884.213163.1059
9898.151  162.869908.605162.34019936.486162.22929947.429161.8566 9962.02162.2482
9980.138161.87479999.765 160.88810009.55161.297710035.98 161.18910043.11161.6164
10053.81162.812810095.59163.383710122.93164.944610133.13165.137610139.93 165.612
10160.25165.927810183.73 167.82610203.85170.513610230.69173.5072 10235.1174.3712
#Mann= 3 , 0 , 0
 9764.93  0.0862       0 9764.93  0.0862       0 10235.1  0.0862       0
#XS Ineff= 2 , 0
       0                               0
Bank Sta=9764.93,10235.1
Exp/Cntr=0.3,0.1

Type RM Length L Ch R = 1 ,   11003,198.125800,198.125800,198.125800
XS GIS Cut Line= 6
1232530.36313164618372.5311997181232434.67735069618354.039707223
1232322.35201971618327.0840236321232270.36331027618319.640050456
1232179.85889617618299.3985992681232055.91251418618283.502545952
#Sta/Elev= 30
9758.374170.00989797.558167.22339834.315163.57829844.339163.63919861.098162.7857
9894.838158.81029972.421157.24329998.961155.716910005.58 155.83610018.83157.4267
10035.56157.417410059.09158.315610065.82160.7199 10075.9160.797510089.35163.0527
10092.71163.093310099.44161.135210106.16160.397410116.25160.6068 10122.9160.1245
10149.49160.998310159.46160.6446 10166.1160.8529 10177.4162.840110192.52164.4171
10202.42164.354210215.61   166.1 10232.1166.8171 10238.7166.650410241.62167.1621
#Mann= 3 , 0 , 0
9758.374  0.0943       09758.374  0.0943       010241.62  0.0943       0
#XS Ineff= 2 , 0
       0                               0
Bank Sta=9758.374,10241.62
Exp/Cntr=0.3,0.1

Type RM Length L Ch R = 1 ,10804.87,198.125800,198.125800,198.125800
XS GIS Cut Line= 6
1232552.76106554618117.4222774621232405.69792035618127.700157951
1232309.16584557618139.2888016371232274.22023069618139.829041583
 1232206.9626731618145.5462893181232035.42772144618164.478412104
#Sta/Elev= 30
9740.161176.19019788.024166.21279814.335162.08099834.068159.88499916.425157.6582
9926.338156.97359936.251154.58549939.555154.31039965.991154.72389975.904154.3962
9982.512153.13039995.656 152.81610015.35153.179710025.21154.182810044.97154.0271
10054.84154.617210064.72152.495810068.02 152.328 10074.6153.364710091.07157.5174
10097.67158.241910110.88156.681910127.38  157.7310143.89156.382910173.59156.4748
 10186.8156.8948 10206.6158.694810233.01159.786110252.81161.464610259.84161.3687
#Mann= 3 , 0 , 0
9740.161  0.0712       09740.161  0.0712       010259.84  0.0712       0
#XS Ineff= 2 , 0
       0                               0
Bank Sta=9740.161,10259.84
Exp/Cntr=0.3,0.1

Type RM Length L Ch R = 1 ,10606.75,198.125700,198.125700,198.125700
XS GIS Cut Line= 6
 1232532.6223623617835.8963697851232456.01281298617862.210939411
1232379.14211329617894.0055709681232289.88311967617940.126652752
1232191.75159287617999.5864238541232036.21525612618061.262644438
#Sta/Elev= 30
9726.538185.0839 9751.13183.04789759.198180.03369773.074 176.1319804.295169.8035
 9818.42168.10369861.025 165.5219868.126162.94739875.226157.55879878.777155.5008
9882.327154.93579885.878152.94029889.428151.88939907.643150.82399918.594149.2433
9933.557149.31369981.621146.17579989.086144.685910000.66144.228410059.18146.5211
10093.05147.232910100.51146.829910157.96148.467510175.84148.244610200.49152.6002
10217.95153.133810235.41154.667910245.89154.577910256.36156.140510273.44155.5195
#Mann= 3 , 0 , 0
9726.538   0.085       09726.538   0.085       010273.44   0.085       0
#XS Ineff= 2 , 0
       0                               0
Bank Sta=9726.538,10273.44
Exp/Cntr=0.3,0.1

Type RM Length L Ch R = 1 ,10408.62,198.125800,198.125800,198.125800
XS GIS Cut Line= 6
1232389.52191948617646.3026332311232243.78385595617725.340889302
1232190.93888276 617765.782149431232077.42226728617872.388133259
1232010.14284608617917.1902357611231925.19792618617961.238673737
#Sta/Elev= 30
9717.426183.87959742.222 181.4749764.108176.89959775.051172.48989782.346166.7761
9789.641163.75119815.814 161.3659827.713162.33429849.865153.64149859.753152.9935
9865.866 151.0819877.083150.07299901.088145.63649917.258 145.5849929.867143.8476
9955.725 142.06110021.87 142.19810031.37141.508810045.98142.707110096.02144.2995
10148.63149.944110160.27149.187510184.72150.9138   10210150.976910213.76151.8144
10228.72158.121910243.34161.1592 10254.3161.382510265.27162.818110282.54167.3133
#Mann= 3 , 0 , 0
9717.426   0.085       09717.426   0.085       010282.54   0.085       0
#XS Ineff= 2 , 0
       0                               0
Bank Sta=9717.426,10282.54
Exp/Cntr=0.3,0.1

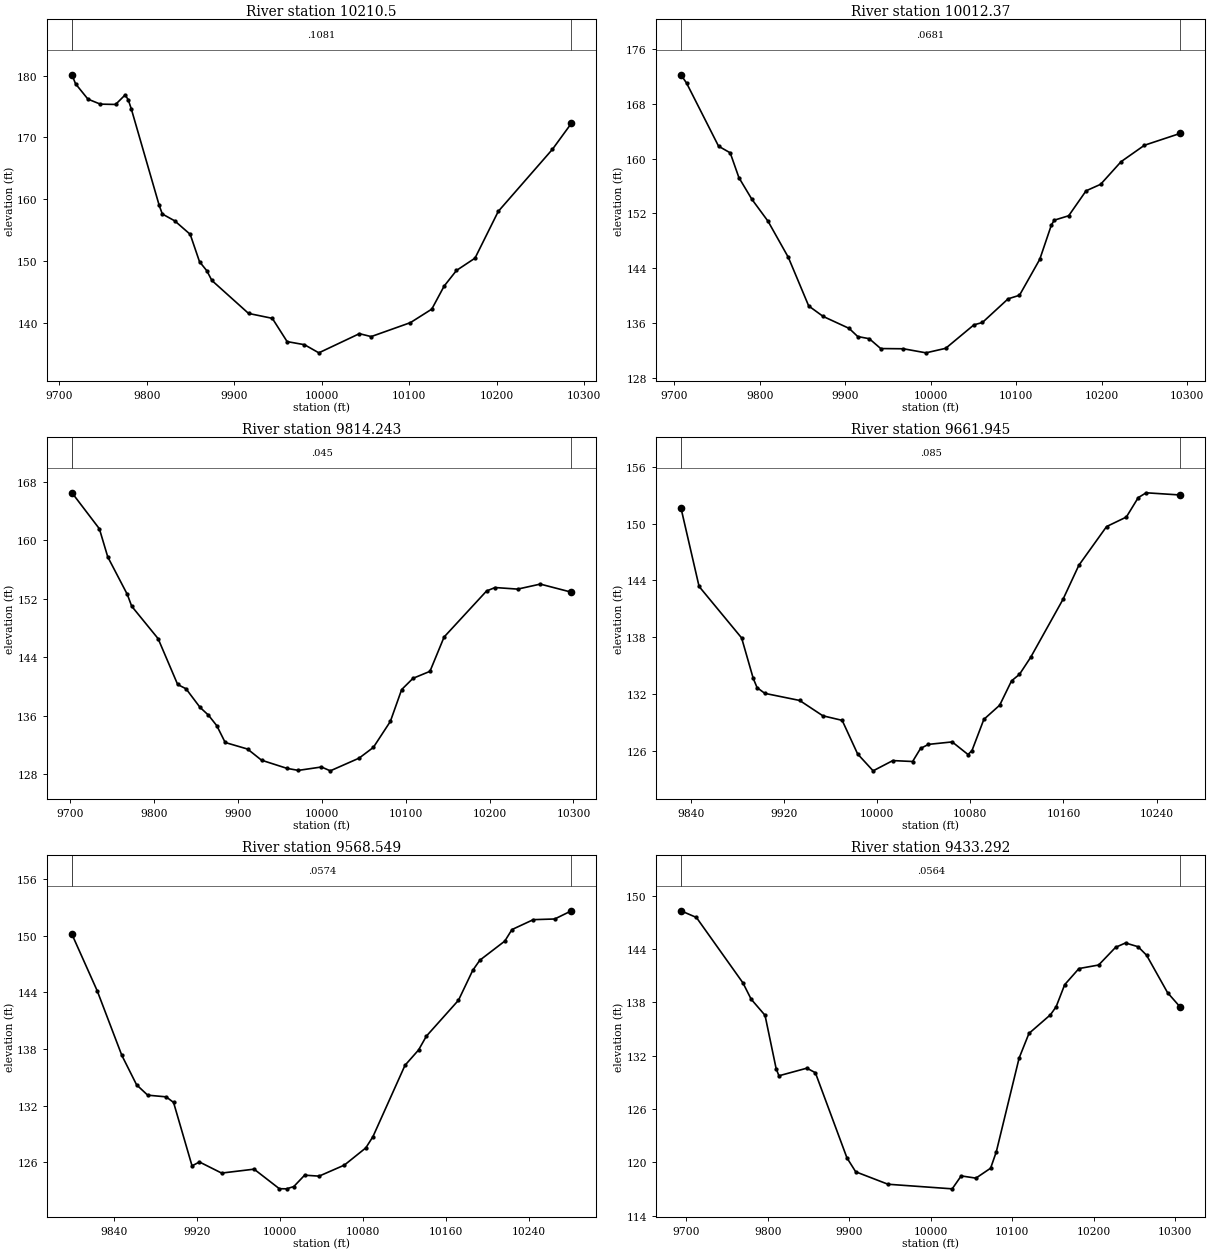
Type RM Length L Ch R = 1 , 10210.5,198.125800,198.125800,198.125800
XS GIS Cut Line= 6
1232334.91355959617549.4707377981232143.90839276617625.458250854
1232103.06914786 617635.662802431232039.25253313617639.460060514
 1232000.9171307617647.9874319041231795.65719559617727.279968641
#Sta/Elev= 30
9714.485180.14759718.571178.69449732.743176.20839746.915175.39679764.348 175.347
9775.259176.88459778.802176.11299782.345174.61559814.232159.00159817.775157.6185
9831.947156.51199849.662154.32519860.291 149.8999868.633148.43819874.427 146.863
9916.352141.53169943.525140.73449960.434 136.9729980.285136.46889996.702135.1529
10043.07138.255210056.51137.781510101.38140.040410125.79142.225410139.92145.9529
10154.05148.486110175.21150.474210201.77158.036810263.74168.0916 10285.5172.3174
#Mann= 3 , 0 , 0
9714.485  0.1081       09714.485  0.1081       0 10285.5  0.1081       0
#XS Ineff= 2 , 0
       0                               0
Bank Sta=9714.485,10285.5
Exp/Cntr=0.3,0.1

Type RM Length L Ch R = 1 ,10012.37,198.125800,198.125800,198.125800
XS GIS Cut Line= 6
1232265.36480331617402.1930590951232046.86787379617459.113690236
1232009.76430078617465.045716004 1231936.4575553 617470.46167779
1231878.41178661617480.929784474  1231696.838478617530.477374488
#Sta/Elev= 30
9707.933172.22169714.578171.00729751.976 161.8099765.575160.84179775.774157.2211
9790.866154.07989809.772150.87349833.571145.59389857.369138.51369874.275136.9854
9904.613135.24489914.726134.0522 9928.21133.7381 9941.58132.3013 9968.16132.2702
9994.499131.677310017.53132.335110050.51135.752310060.51136.104210090.52139.5503
10103.85140.072410127.54145.310610141.08150.291310144.46151.018510161.38 151.666
10181.69155.300710198.74 156.25210222.64159.552310249.95161.944910292.05163.6846
#Mann= 3 , 0 , 0
9707.933  0.0681       09707.933  0.0681       010292.05  0.0681       0
#XS Ineff= 2 , 0
       0                               0
Bank Sta=9707.933,10292.05
Exp/Cntr=0.3,0.1

Type RM Length L Ch R = 1 ,9814.243,152.298800,152.298800,152.298800
XS GIS Cut Line= 6
1232241.91376679617221.1618203051232008.20989153617262.799353068
1231970.88325601617272.3574184631231931.59061375617286.275303048
1231892.69681981617297.2920122591231661.77147852617352.309111772
#Sta/Elev= 30
9702.298166.51859734.979161.58959744.976157.73659768.304152.59749773.497150.9916
9804.961146.55499828.289140.27619838.286139.68629854.949 137.1449864.946136.0828
9874.944134.63349884.941132.33539911.601131.43819928.264129.91259958.558128.7945
9972.105128.51739999.735128.981910010.21128.455410044.52130.191710061.56131.6645
10081.79135.216510095.28139.580610108.77141.117910129.01142.076110145.87146.7766
10196.46153.071610206.58153.548310233.56 153.33210260.54154.017910297.71152.9072
#Mann= 3 , 0 , 0
9702.298   0.045       09702.298   0.045       010297.71   0.045       0
#XS Ineff= 2 , 0
       0                               0
Bank Sta=9702.298,10297.71
Exp/Cntr=0.3,0.1

Type RM Length L Ch R = 1 ,9661.945,93.395600,93.395600,93.395600
XS GIS Cut Line= 3
1232126.73281175617105.1980412451231960.36617914617130.623045489
1231708.87011379617198.056418583
#Sta/Elev= 30
9831.702151.67319847.299143.37229883.807137.94259893.764133.68239897.083132.7016
9903.721132.09919933.591131.35269953.505129.73529970.099129.25269983.375125.7085
9996.651123.931810013.56125.012510030.54124.916110037.33126.289110044.13 126.721
10064.51126.981610078.09125.652710081.49 126.06810091.68129.356610105.27 130.853
10115.46133.419610122.25134.104410131.78135.884110159.61142.0144 10173.2145.6013
10196.98149.682110213.96 150.68710224.15152.731510230.95153.245110260.38153.0105
#Mann= 3 , 0 , 0
9831.702   0.085       09831.702   0.085       010260.38   0.085       0
#XS Ineff= 2 , 0
       0                               0
Bank Sta=9831.702,10260.38
Exp/Cntr=0.3,0.1

Type RM Length L Ch R = 1 ,9568.549,135.257200,135.257200,135.257200
XS GIS Cut Line= 4
1232122.78139144616964.9226201771231989.92359871 617021.41425404
1231873.84191179617062.7202728841231669.35591069617126.930852965
#Sta/Elev= 30
9799.203150.16319823.588144.16639847.315137.32619861.575134.1994 9872.27133.1056
9890.096132.92779897.226132.33399915.052125.60699922.182126.02269943.572124.8444
9974.914125.25959999.254123.188410006.25123.172910013.22123.416410023.67124.6212
 10037.6  124.5210061.97125.688810082.67127.512710089.54 128.70210120.49136.2724
10133.58137.898810141.12 139.36410172.07143.169510185.83146.340510192.71147.4185
10216.78149.445210223.66150.665110244.29151.718110264.92151.787210281.11152.6585
#Mann= 3 , 0 , 0
9799.203  0.0574       09799.203  0.0574       010281.11  0.0574       0
#XS Ineff= 2 , 0
       0                               0
Bank Sta=9799.203,10281.11
Exp/Cntr=0.3,0.1

Type RM Length L Ch R = 1 ,9433.292,198.125800,198.125800,198.125800
XS GIS Cut Line= 6
1232179.11567455616814.102274695 1232093.1235999616833.005632148
1232002.73282689616861.1300035831231943.44779155616886.649603843
 1231826.6441813616948.0617727471231606.02008866617025.398172179
#Sta/Elev= 30
9693.447148.28569712.479147.53459769.585140.17699779.663138.34349796.696136.5336
9810.346130.53159813.759129.72819848.093130.58469858.505130.07099897.279120.4915
9907.995118.92979947.621117.530110026.45117.012910037.48118.466710055.55118.2164
10073.59 119.33410080.58121.180310108.56131.713610120.65134.491210147.02136.5894
10154.02137.492610164.51139.973710181.99141.786810206.21142.186610226.97144.1733
10239.16144.666110254.64 144.24210265.02143.288310290.83139.070210306.59137.4266
#Mann= 3 , 0 , 0
9693.447  0.0564       09693.447  0.0564       010306.59  0.0564       0
#XS Ineff= 2 , 0
       0                               0
Bank Sta=9693.447,10306.59
Exp/Cntr=0.3,0.1

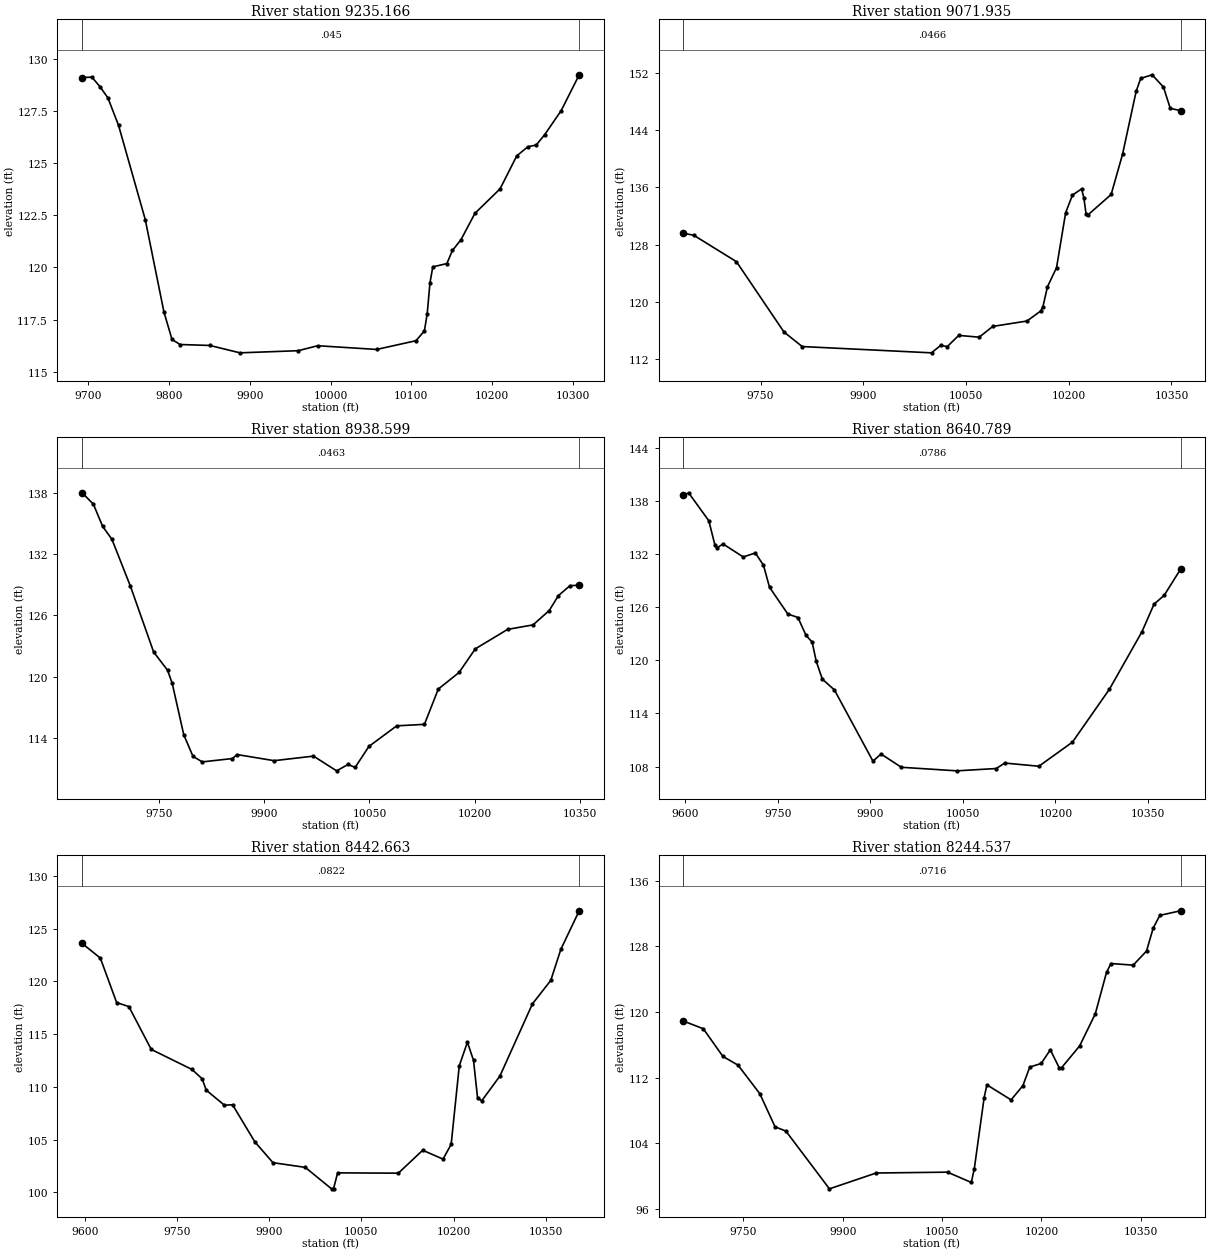
Type RM Length L Ch R = 1 ,9235.166,163.231400,163.231400,163.231400
XS GIS Cut Line= 6
1232093.79951378616676.9154577281231992.23281125616689.765253076
 1231895.3075697616711.7775772571231808.63854374616739.201242228
1231611.34137157616808.9446142661231502.78537176616843.404893104
#Sta/Elev= 30
9692.081 129.0979704.189129.1156 9714.11128.66659724.031128.12479737.259126.8038
9770.329122.29299793.478117.8642  9803.5116.54539813.533116.30479850.389116.2591
 9887.66115.90579959.873116.00849983.916116.246310056.97116.068310105.69116.4868
10116.13116.953210119.61117.771810123.09119.270210126.57120.024110143.97120.1833
10150.93120.813610161.37121.319510178.82122.592110209.92 123.76410230.57125.3435
10244.34125.780710254.67125.862410264.99126.350510285.65127.514610307.95129.2289
#Mann= 3 , 0 , 0
9692.081   0.045       09692.081   0.045       010307.95   0.045       0
#XS Ineff= 2 , 0
       0                               0
Bank Sta=9692.081,10307.95
Exp/Cntr=0.3,0.1

Type RM Length L Ch R = 1 ,9071.935,133.335800,133.335800,133.335800
XS GIS Cut Line= 6
1232119.60392526616620.2518507121232017.13451224616612.456063932
1231855.86107884616585.0755388671231800.98180511 616582.06102598
   1231733.64681616588.5606920761231400.95629723616641.094329715
#Sta/Elev= 30
9637.362129.59659652.256129.33629714.772125.63749784.195115.80769810.795113.7797
9999.586112.901110012.81113.931810022.74 113.78510039.33115.336710069.23115.0909
10089.16 116.59510138.98117.345910158.91118.734210162.23119.323910168.87122.1265
10182.16124.794910195.44 132.46910205.41134.941110218.69135.798710222.01134.5646
10225.34 132.26210228.66132.222910261.87135.021710278.48140.617510298.41149.4405
10305.05151.232910321.66151.743510338.27  150.0310348.23147.042510363.24146.7422
#Mann= 3 , 0 , 0
9637.362  0.0466       09637.362  0.0466       010363.24  0.0466       0
#XS Ineff= 2 , 0
       0                               0
Bank Sta=9637.362,10363.24
Exp/Cntr=0.3,0.1

Type RM Length L Ch R = 1 ,8938.599,297.810100,297.810100,297.810100
XS GIS Cut Line= 3
1232094.47728136616484.4460144841231799.33839247616447.987681155
1231389.61617023616487.918236693
#Sta/Elev= 30
9640.134138.02359656.227136.9081 9669.45134.72699682.673133.46549709.119128.8559
9742.177122.41529762.011120.62539768.623119.35959785.152114.29619798.375112.1746
9811.598111.63829854.573111.96669861.184112.35799914.077111.75759970.182 112.205
10003.15110.761610019.63111.390910029.52111.092610049.29113.159310088.85115.1729
10128.41115.318710148.19 118.77910177.85120.407910200.93122.720410247.08124.6308
10283.34125.072110306.41126.4777 10319.6127.951110336.08128.916710349.18128.9574
#Mann= 3 , 0 , 0
9640.134  0.0463       09640.134  0.0463       010349.18  0.0463       0
#XS Ineff= 2 , 0
       0                               0
Bank Sta=9640.134,10349.18
Exp/Cntr=0.3,0.1

Type RM Length L Ch R = 1 ,8640.789,198.125800,198.125800,198.125800
XS GIS Cut Line= 6
1232270.62666189616282.6505221351232151.20776631616281.129471217
1231943.93444742616267.5991884221231814.63809103616285.781105757
1231622.08358221616232.2202568151231474.47606587616224.285924518
#Sta/Elev= 30
9596.735138.65789605.129138.9641 9637.94 135.7989647.784133.06389651.065132.7184
9660.908 133.1799693.719131.70699713.406132.15329726.557130.77429736.425128.2688
9766.031125.25529782.479124.85619795.638122.82619805.506122.08099812.085119.9247
9821.954117.89219841.691116.65699904.154108.60569917.283109.41529950.182107.9136
10040.34 107.51110104.09107.772810117.93108.390910173.31108.032710227.81110.7621
10287.71116.741910340.43123.234610360.12126.370110376.52127.358510403.12130.3199
#Mann= 3 , 0 , 0
9596.735  0.0786       09596.735  0.0786       010403.12  0.0786       0
#XS Ineff= 2 , 0
       0                               0
Bank Sta=9596.735,10403.12
Exp/Cntr=0.3,0.1

Type RM Length L Ch R = 1 ,8442.663,198.125700,198.125700,198.125700
XS GIS Cut Line= 6
1232327.69752164616066.8085179641232042.21816985616102.534823305
1231970.90955861 616102.979756391231880.43892177616094.009458818
1231829.53088546616096.1285776311231524.00021682616134.798264416
#Sta/Elev= 30
 9595.52123.61289625.206122.22179651.731118.00529671.624117.62179708.096113.5592
9774.354111.6605 9790.86110.77579797.462109.70269827.173108.26889840.355108.3147
9876.547 104.8049906.094102.82269958.607 102.37810001.46100.341510004.76100.3709
10011.35101.8569 10110.1101.826510149.79104.000610182.86103.159710196.09104.5586
10209.31112.011410222.54114.245610232.46112.524410239.08108.951810245.89108.6929
10275.45111.038710328.37117.883410358.13120.097210374.66123.062810404.47126.7051
#Mann= 3 , 0 , 0
 9595.52  0.0822       0 9595.52  0.0822       010404.47  0.0822       0
#XS Ineff= 2 , 0
       0                               0
Bank Sta=9595.52,10404.47
Exp/Cntr=0.3,0.1

Type RM Length L Ch R = 1 ,8244.537,198.125800,198.125800,198.125800
XS GIS Cut Line= 6
1232138.09216321615894.5845891241231923.38785198615899.329435796
1231849.13511875615915.0486639291231779.33420509615993.107545465
1231718.56519774616033.6661592131231447.52015933616109.417769134
#Sta/Elev= 30
 9659.41118.90559689.476117.96339719.011114.59699741.982113.52179774.798 110.045
 9797.77106.01389814.178105.48849879.93498.448629950.482100.378210058.28100.4827
10094.2199.2257710098.77100.914510113.61109.5755 10117.8111.127110154.26109.2963
10172.11111.023510182.47113.289610199.75113.732610213.57115.394910227.36113.1511
10230.75113.236410257.82115.868710281.51119.788610298.43124.840210305.15125.9179
10338.71125.720710358.84127.435710368.91 130.23310378.98131.790210410.27132.3494
#Mann= 3 , 0 , 0
 9659.41  0.0716       0 9659.41  0.0716       010410.27  0.0716       0
#XS Ineff= 2 , 0
       0                               0
Bank Sta=9659.41,10410.27
Exp/Cntr=0.3,0.1

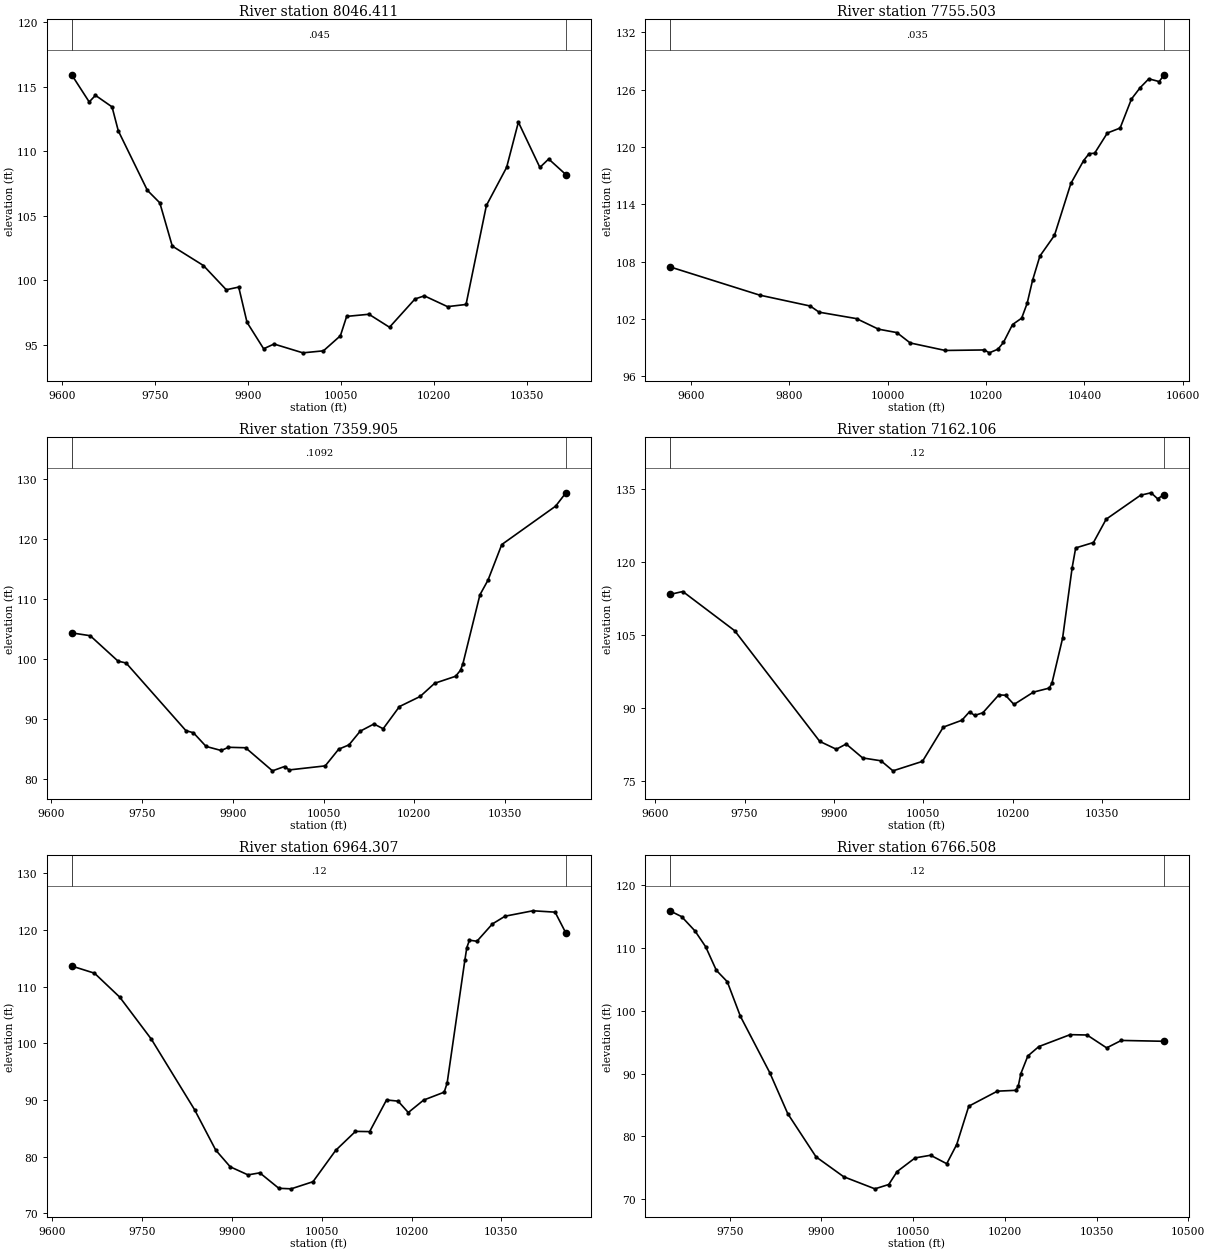
Type RM Length L Ch R = 1 ,8046.411,290.908600,290.908600,290.908600
XS GIS Cut Line= 6
1232106.18516597615841.3710375581231774.74522836615773.585144755
1231701.32245277615784.0611940241231665.38882053615794.895599817
1231495.29146995615885.1062603331231353.99470447615947.430222893
#Sta/Elev= 30
9616.197 115.9339644.449113.82449654.496114.33839681.286113.44259691.332111.5879
9738.214106.97299758.307     1069778.399102.6474 9828.63101.13819865.46799.25899
9885.55999.465669898.95496.731319925.74494.681919942.48895.048929989.041 94.3658
10022.1694.5211310049.5395.6892110059.6397.1930610095.5797.3584210128.74 96.3505
10169.8998.5444210184.9498.78568 10222.3 97.949410252.18  98.11810284.99105.7979
10317.58108.746810336.57112.258910371.23108.746710385.44109.399210413.25108.1886
#Mann= 3 , 0 , 0
9616.197   0.045       09616.197   0.045       010413.25   0.045       0
#XS Ineff= 2 , 0
       09942.852        10099.97       0
Bank Sta=9616.197,10413.25
Exp/Cntr=0.3,0.1

Type RM Length L Ch R = 1 ,7755.503,395.597800,395.597800,395.597800
XS GIS Cut Line= 5
1232022.04109344615715.6385153981231636.13896772615587.971646726
1231489.12863412 615549.284716831231391.44413617615534.777118132
1231084.06061468615696.251570016
#Sta/Elev= 30
 9557.64107.46659740.065104.50979842.902103.36739861.015102.72319937.041102.0487
9981.639100.944810018.96100.5892 10046.199.5036910117.3198.7181710196.9298.77179
10206.8798.4691610224.4698.8514510235.5799.55346 10254.1101.430510272.63102.0976
10283.75 103.64210294.87106.069410309.69108.592110339.34110.7631 10372.7116.1986
10398.64118.589710409.76119.317210420.87119.348810446.81121.469210472.76 121.989
10495.79125.025910513.52 126.21610531.06127.138210552.22126.8502 10562.1127.5616
#Mann= 3 , 0 , 0
 9557.64   0.035       0 9557.64   0.035       0 10562.1   0.035       0
#XS Ineff= 2 , 0
       09933.877        10057.42       0
Bank Sta=9557.64,10562.1
Exp/Cntr=0.3,0.1

Type RM Length L Ch R = 1 ,7359.905,197.798900,197.798900,197.798900
XS GIS Cut Line= 6
1231693.37230795615003.0863289391231599.58342257615103.393039182
1231455.44169486615298.8265440321231379.07845259615382.203198627
1231269.75672162615474.9701571171231120.66653809615576.339020014
#Sta/Elev= 30
 9633.57104.35059664.169103.88299710.24199.652779723.53499.347019822.35888.10816
9834.89887.743139855.77985.47703 9880.7284.802179892.83485.332999921.09985.25673
9965.51681.419579985.43982.139629993.22781.5713610052.7782.2433810075.0185.01632
10092.0685.73496 10110.688.0114110133.3289.2088610148.5788.4170710175.49 92.1039
10209.67 93.780310233.7795.9766710268.3397.1376810276.4598.1473310280.4699.23988
10308.58110.6872 10321.9113.114110344.65119.033510433.74125.420510450.76127.6416
#Mann= 3 , 0 , 0
 9633.57  0.1092       0 9633.57  0.1092       010450.76  0.1092       0
#XS Ineff= 2 , 0
       0                               0
Bank Sta=9633.57,10450.76
Exp/Cntr=0.3,0.1

Type RM Length L Ch R = 1 ,7162.106,197.798900,197.798900,197.798900
XS GIS Cut Line= 6
1231530.43644104614878.4883130681231372.04932815615068.189590752
1231272.18061516615221.4031393531231218.55174717 615288.53990002
1231104.41788125615400.4966533781230984.01141897615494.803547308
#Sta/Elev= 30
9624.672113.36829646.405113.96959733.392105.93119876.10783.214899903.93581.59636
9920.469 82.67599948.04879.820389978.90479.22935    999977.1677710048.4679.11212
10083.41 86.142510114.5887.5472510127.4589.3015610136.0388.5303810149.8289.09104
10176.6292.7617310187.7792.67852   1020290.7887710234.6493.32353 10261.394.15253
10265.7495.1852510283.51104.358910299.61118.882110305.51122.914410335.32124.0253
10356.62128.807710414.37 133.73210432.03134.232910442.93133.000810453.82 133.857
#Mann= 3 , 0 , 0
9624.672    0.12       09624.672    0.12       010453.82    0.12       0
#XS Ineff= 2 , 0
       0                               0
Bank Sta=9624.672,10453.82
Exp/Cntr=0.3,0.1

Type RM Length L Ch R = 1 ,6964.307,197.798900,197.798900,197.798900
XS GIS Cut Line= 6
 1231400.4087528 614779.055375011231334.06205955 614845.29653047
1231125.48785523615076.6134098021231044.54433024615160.544879824
1230939.63024735615257.596357688 1230814.1156998615357.631878659
#Sta/Elev= 30
9632.465113.65439670.541112.38929712.734108.16119765.546100.7414 9837.7788.29476
 9873.01 81.18259897.27878.227569926.90176.80642 9946.6577.16494 9978.3874.44269
    999974.3442110035.4975.6031710073.3881.1311710106.46 84.481210130.0984.43934
10158.2990.0258910177.6189.8149910194.6387.8072610220.3190.0075110254.59 91.3988
10259.51 93.002810289.03114.631410292.41116.915910296.81 118.21410309.27118.0229
10335.08121.076910356.32122.446410402.77123.400310439.84123.157510457.92119.4531
#Mann= 3 , 0 , 0
9632.465    0.12       09632.465    0.12       010457.92    0.12       0
#XS Ineff= 2 , 0
       0                               0
Bank Sta=9632.465,10457.92
Exp/Cntr=0.3,0.1

Type RM Length L Ch R = 1 ,6766.508,197.798900,197.798900,197.798900
XS GIS Cut Line= 6
1231268.38876148614678.0989110581231253.50048465614686.136419103
1231132.85182446614792.1425191761230888.55326065615022.115390137
1230773.04514757615115.0764149581230653.91242954615201.090422779
#Sta/Elev= 30
9652.193115.96059671.517115.02279693.298112.74629710.767110.22369728.237 106.463
9746.076104.65469767.54399.140589815.58390.14535 9845.03 83.60299891.28876.71727
9936.503 73.54879987.59271.6183410010.1972.3096210023.9374.3791710053.3276.54976
10078.6376.9753810105.0375.6250910121.3678.6885710141.0584.7962510187.8887.19613
 10217.787.3267210221.9687.9629510226.2289.98233 10237.792.8086310255.6594.30547
10306.8996.2066410334.5696.1499610366.5794.09788 10390.695.2845510460.5295.14854
#Mann= 3 , 0 , 0
9652.193    0.12       09652.193    0.12       010460.52    0.12       0
#XS Ineff= 2 , 0
       0                               0
Bank Sta=9652.193,10460.52
Exp/Cntr=0.3,0.1

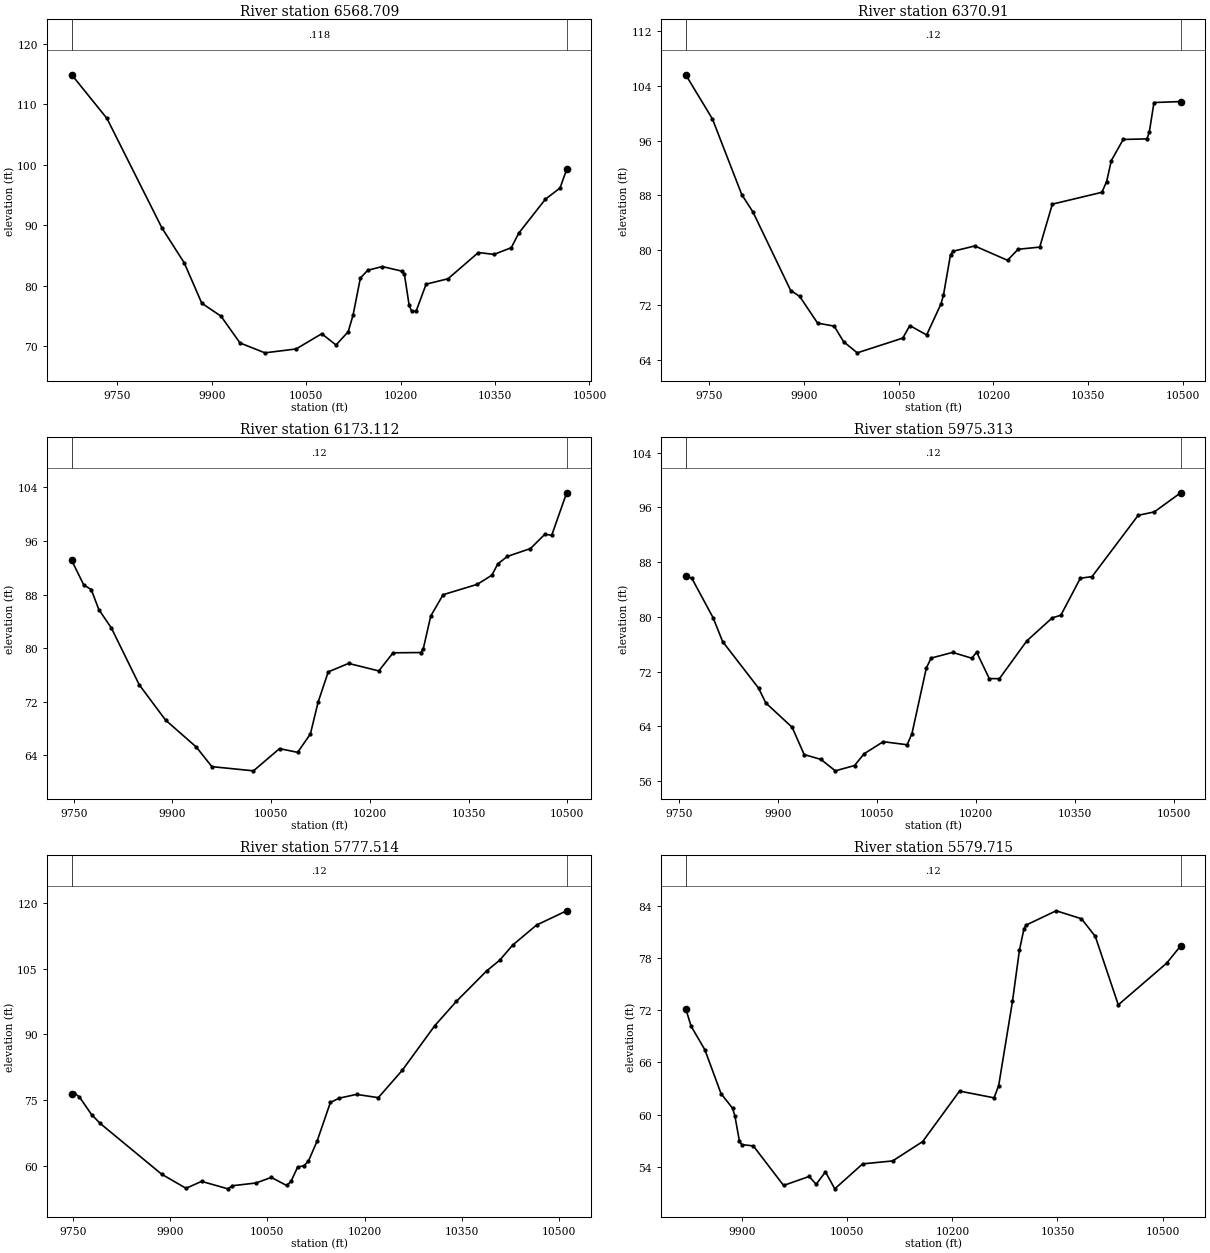
Type RM Length L Ch R = 1 ,6568.709,197.798900,197.798900,197.798900
XS GIS Cut Line= 6
1231176.33130279614593.1248073731231073.49140424614648.480263233
1230938.24061465614734.1490900221230866.78935611614762.802743703
1230817.82203794614788.5668033361230498.03786102614988.433185548
#Sta/Elev= 30
9677.439114.8873 9733.39107.67419820.65689.589699856.307 83.78049884.03677.13477
9914.67174.976549944.82670.55523  9984.468.9235710033.9169.5633210074.6972.07994
10097.3870.2184410116.7372.4122310124.4675.1619710136.0781.2769410147.6882.56904
10170.8983.1866810201.8482.4317310206.01 81.928210213.45  76.86210217.3275.83314
10224.5875.7884110240.5380.2737710275.3581.1699110323.63 85.507110348.39 85.1942
10375.9486.3100510387.5588.6836410430.1194.3245110453.3296.1679110463.8799.25179
#Mann= 3 , 0 , 0
9677.439   0.118       09677.439   0.118       010463.87   0.118       0
#XS Ineff= 2 , 0
       0                               0
Bank Sta=9677.439,10463.87
Exp/Cntr=0.3,0.1

Type RM Length L Ch R = 1 , 6370.91,197.798900,197.798900,197.798900
XS GIS Cut Line= 6
1231038.24752204614440.8785875691230856.42210194614554.967205003
1230819.96981788 614574.458179311230731.29141825  614614.8621445
 1230502.6698488614749.8945808861230358.48761708614829.842881903
#Sta/Elev= 30
9712.569105.62139754.89799.166729801.37688.112369818.97985.59805 9878.8474.11241
9893.05373.260489921.44569.354099947.71668.914999962.59766.641379984.23865.01444
10056.3867.1684510067.4868.9957110094.1567.6240210117.0172.1943810120.8273.46998
10131.9379.3427310136.0679.8506210170.3680.6212610222.2578.5284310238.94 80.1355
10273.24 80.459310293.2186.7278310371.6888.4579510379.1890.0268410386.6893.09833
10405.4496.1762210442.9596.2584910446.7197.2196510454.21101.569210496.46101.7095
#Mann= 3 , 0 , 0
9712.569    0.12       09712.569    0.12       010496.46    0.12       0
#XS Ineff= 2 , 0
       0                               0
Bank Sta=9712.569,10496.46
Exp/Cntr=0.3,0.1

Type RM Length L Ch R = 1 ,6173.112,197.798900,197.798900,197.798900
XS GIS Cut Line= 6
1230896.61158769614284.7158907291230800.66090205614342.692943543
1230611.28294763614469.851242572 1230519.3343842 614527.32158269
1230402.28294453614592.7492118031230250.68435711614668.005200163
#Sta/Elev= 30
9746.98293.090499765.32189.431069776.61988.759059788.13485.774269807.32582.99701
9849.54674.546259889.48469.283969936.21965.258649959.93462.3291310023.1661.70266
10062.6765.0176310090.2664.46055 10109.667.2034110121.2171.9132410136.6976.46597
10167.6477.7316410213.5476.6129810235.24 79.312410277.4479.3562410281.19 79.9442
10292.4784.8064410311.2687.9863910363.1989.5335210385.2990.8900810394.3792.58137
10408.8293.6951210443.9994.8728710465.8297.0029810476.2896.8533210498.99103.1934
#Mann= 3 , 0 , 0
9746.982    0.12       09746.982    0.12       010498.99    0.12       0
#XS Ineff= 2 , 0
       0                               0
Bank Sta=9746.982,10498.99
Exp/Cntr=0.3,0.1

Type RM Length L Ch R = 1 ,5975.313,197.798900,197.798900,197.798900
XS GIS Cut Line= 6
1230794.33213067614153.9393159021230746.29349539614175.170494914
1230576.38316861614256.1226475541230354.24477541614361.083067298
1230231.28794727614411.9366676961230108.59966931614456.750405654
#Sta/Elev= 30
9760.26985.966279769.53585.638599801.81779.86137 9816.2176.387119870.72269.58178
9881.62467.425219921.59963.85838 9939.7759.881949965.20959.173529987.014 57.5044
10016.0758.2787910030.5859.9926510059.6161.76459 10095.961.3125610103.1562.94839
10124.9372.5318510132.1873.9787410164.8474.8064710193.8773.9528110201.1374.84466
10220.2770.9829410235.6370.9679110277.25 76.497710315.7279.8511910328.7580.23398
10358.3385.6393510376.0885.8813210445.9994.8342210470.4495.3321710510.3698.12621
#Mann= 3 , 0 , 0
9760.269    0.12       09760.269    0.12       010510.36    0.12       0
#XS Ineff= 2 , 0
       0                               0
Bank Sta=9760.269,10510.36
Exp/Cntr=0.3,0.1

Type RM Length L Ch R = 1 ,5777.514,197.798900,197.798900,197.798900
XS GIS Cut Line= 6
1230730.32019957614022.3592352691230622.31679946614047.504259661
1230508.09405684614081.2048948111230453.42198628614090.441868588
1230208.37934738614146.8548081371229985.56273994614189.227676794
#Sta/Elev= 30
9748.23176.465489751.83276.65761 9760.0475.721949778.783 71.70239792.259  69.657
 9887.0158.081359924.63754.862879948.58256.443459989.31854.741279995.97355.44979
10032.5856.0739310056.1857.3501410079.8155.5075610086.5656.4328710096.6859.67042
10106.8160.0480810113.5661.0957110127.0665.7191610147.3174.45115 10160.875.43385
 10187.776.3011410221.2875.5538910258.21 81.789810308.4591.9871110341.85 97.5443
10388.61104.505810408.64106.929110428.68 110.38810465.42 114.94210511.94118.2089
#Mann= 3 , 0 , 0
9748.231    0.12       09748.231    0.12       010511.94    0.12       0
#XS Ineff= 2 , 0
       0                               0
Bank Sta=9748.231,10511.94
Exp/Cntr=0.3,0.1

Type RM Length L Ch R = 1 ,5579.715,197.798800,197.798800,197.798800
XS GIS Cut Line= 6
1230675.37061447613909.4073103341230582.94965711613902.869219959
1230431.96004871613879.2648223191230343.28307679613870.491507441
1230196.90810475613862.8630698771229971.79437795613857.338121161
#Sta/Elev= 30
9819.47472.202979827.09870.182139846.83567.452259869.869 62.41139886.32260.72967
9889.61259.850389896.19456.909769899.48456.541479915.97156.38812 9959.1351.83766
9995.64952.8718710005.6151.97267 10018.9 53.398210032.1851.4471410071.9954.32176
10114.8554.65979 10157.756.8958810210.2662.7029710259.5461.9264610266.1163.34417
10285.8273.0456310295.6878.9015410302.2581.4195410305.5381.83014 10348.283.46433
 10384.382.5434510403.9980.51398 10436.872.6326110505.7277.4207210525.8379.42524
#Mann= 3 , 0 , 0
9819.474    0.12       09819.474    0.12       010525.83    0.12       0
#XS Ineff= 2 , 0
       0                               0
Bank Sta=9819.474,10525.83
Exp/Cntr=0.3,0.1