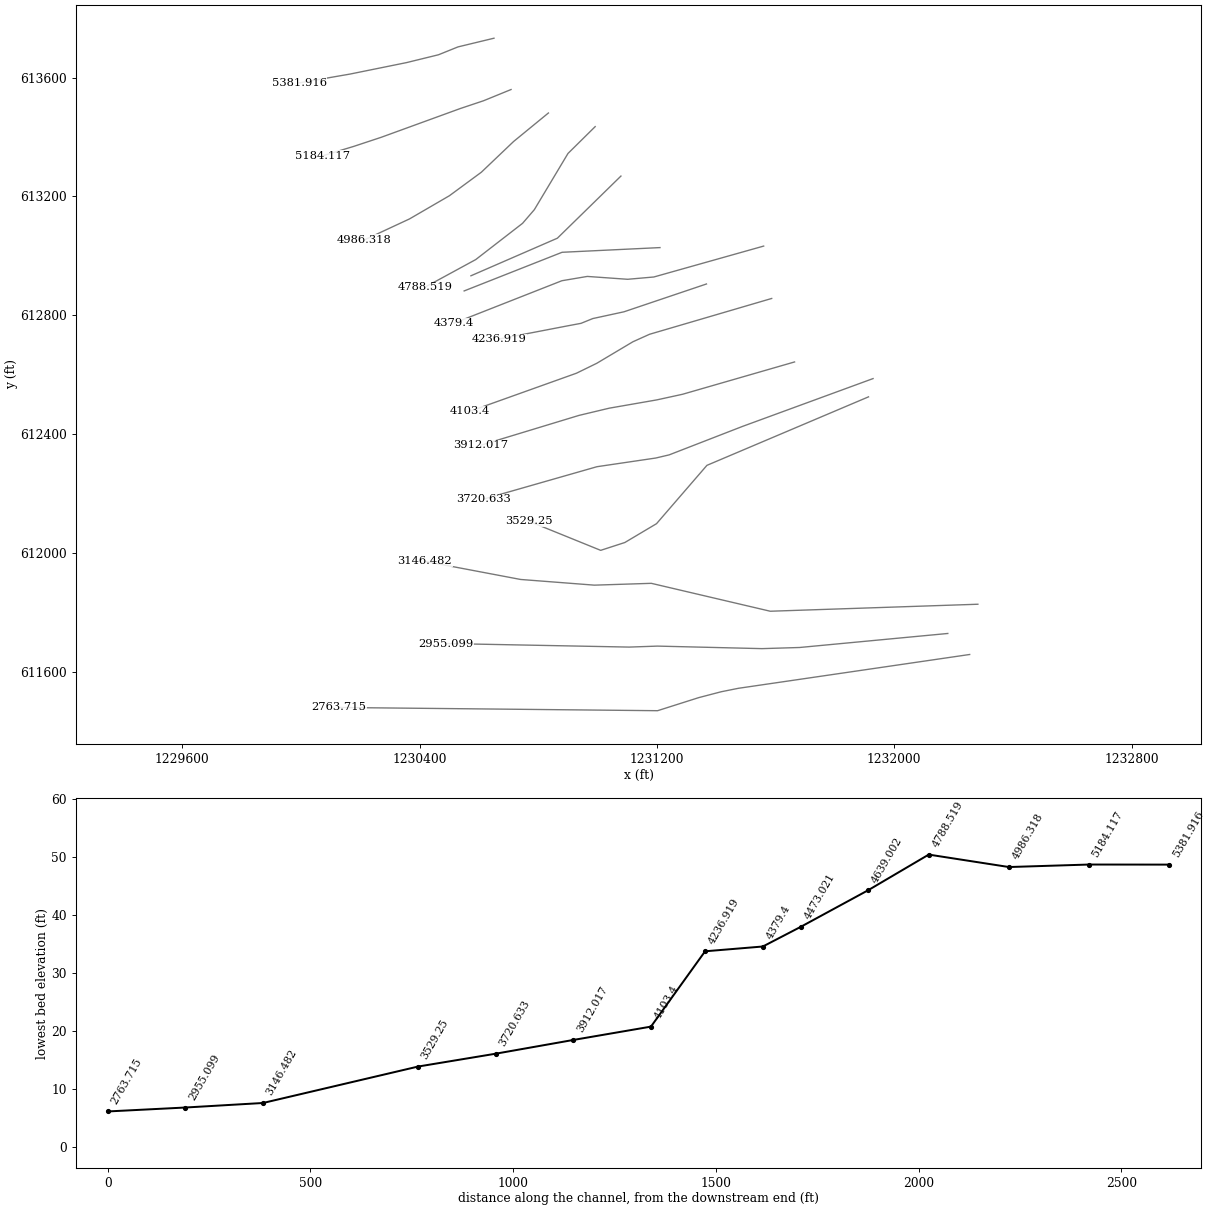
HEC-RAS study 301_ras.prj: 301

--- 301_ras.g01 (geometry) --- (continued)

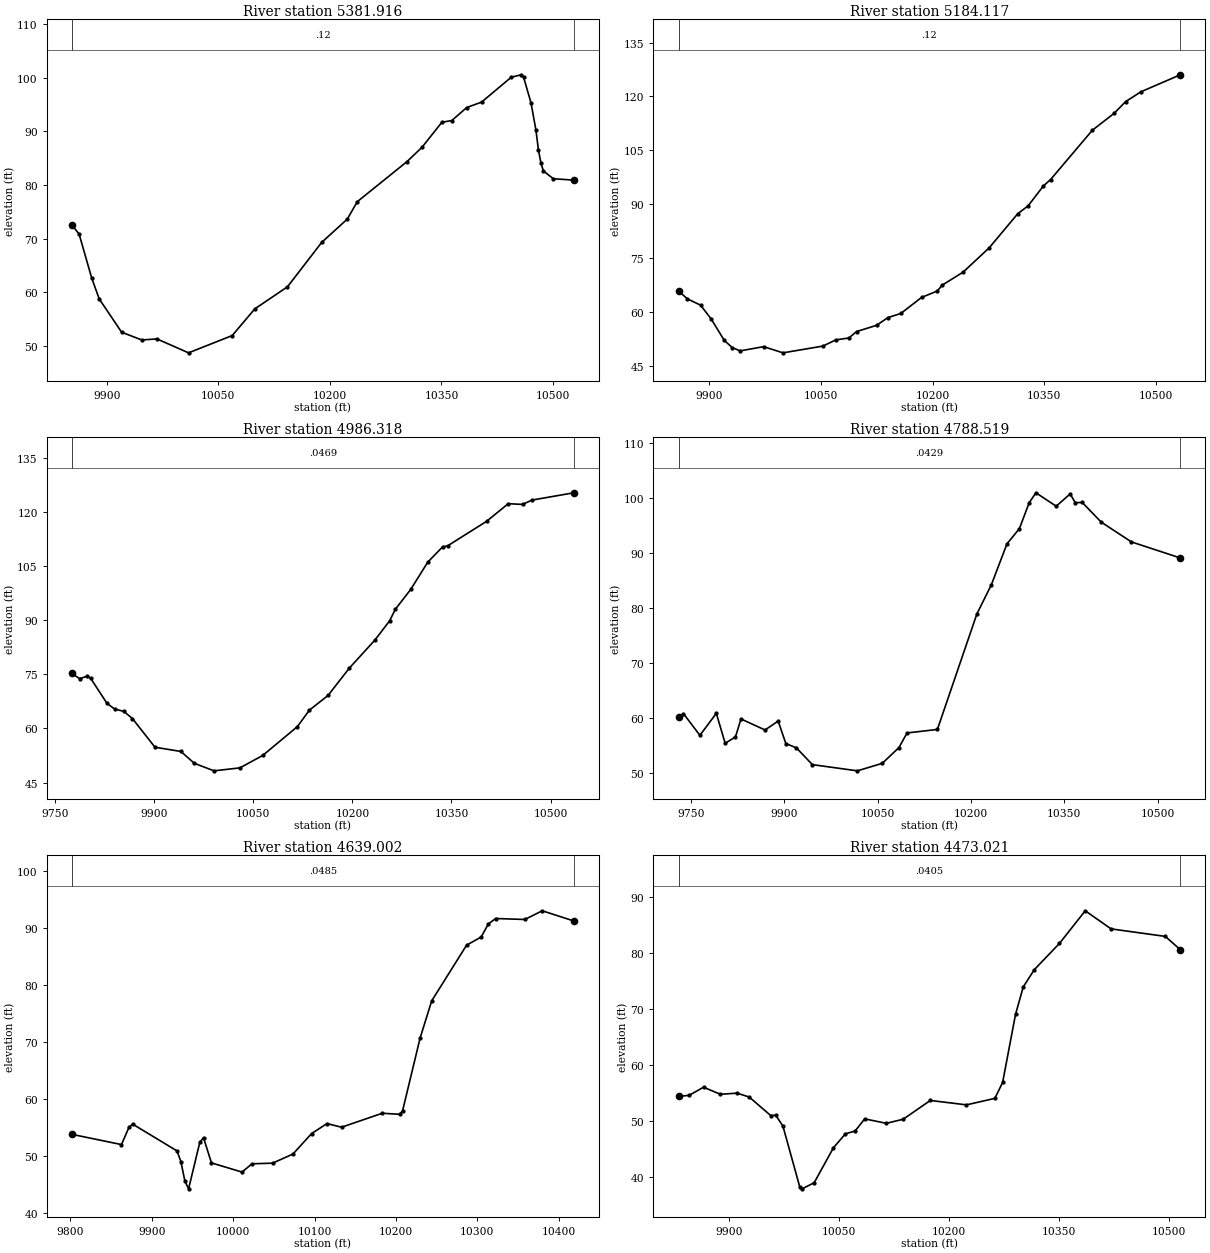
Type RM Length L Ch R = 1 ,5381.916,197.798900,197.798900,197.798900
XS GIS Cut Line= 6
1230650.77935655613732.2064555731230529.34049529613702.944347933
1230463.63771814613676.4985047131230356.18240994  613650.2342778
1230165.08035401613611.5400884151229994.18726215613582.024954781
#Sta/Elev= 30
9853.272 72.50149862.77570.815089879.57862.668439889.65958.759789919.90452.51419
9946.955 51.06239967.37851.2597210009.9448.6591110068.6951.8873410099.0856.87011
10142.9960.9880310189.0669.2864910223.4873.6330810236.8776.8746510303.8184.36729
 10323.987.0308410350.6891.7100910364.0292.0238910383.9994.4492810403.9795.45863
10443.92 100.10910457.24100.567710460.57100.103510470.5695.3058210477.2290.17841
10480.5586.4991710483.8884.09997 10487.282.6102110500.5281.1631510528.1680.90129
#Mann= 3 , 0 , 0
9853.272    0.12       09853.272    0.12       010528.16    0.12       0
#XS Ineff= 2 , 0
       0                               0
Bank Sta=9853.272,10528.16
Exp/Cntr=0.3,0.1

Type RM Length L Ch R = 1 ,5184.117,197.798900,197.798900,197.798900
XS GIS Cut Line= 6
1230708.30129634613559.6406362231230615.81532317613521.980356306
1230537.07000494613495.7084871531230270.30901539613398.896476135
1230177.80073929613368.3722834291230072.34399676613336.550339639
#Sta/Elev= 30
9858.62965.876799870.54163.686329888.25261.93381 9902.4258.120489920.13152.12406
9930.757 50.14529941.38449.216039972.949  50.394    999948.6731610052.5750.55011
10070.0252.2739710087.4752.8069810097.9454.6043410124.9256.3394610139.82 58.4727
10157.2759.62053 10185.264.0912610206.1465.8638310213.1267.5331810241.0471.13257
10275.9477.8666810314.3387.3553410328.2689.5563510348.9995.1358210358.4396.86991
10414.63110.598310443.84115.300510459.25 118.54810479.81121.290310532.86126.0356
#Mann= 3 , 0 , 0
9858.629    0.12       09858.629    0.12       010532.86    0.12       0
#XS Ineff= 2 , 0
       0                               0
Bank Sta=9858.629,10532.86
Exp/Cntr=0.3,0.1

Type RM Length L Ch R = 1 ,4986.318,197.798900,197.798900,197.798900
XS GIS Cut Line= 6
1230834.22329015613480.7641793791230716.83183335613384.858790207
1230608.19914238613281.6050101471230500.52874745 613202.54305345
1230365.82773413 613124.442403971230212.79643623613053.463781304
#Sta/Elev= 30
9775.60375.284619786.989 73.83329797.63974.475499803.60173.977139828.51966.96405
9839.94465.428749854.19464.73251 9867.0562.741279901.13754.800479940.41253.61972
9960.59350.343829990.50548.2420810029.71 49.067810064.3552.5233610116.8460.54063
10134.7365.0694910163.0969.1654810195.33 76.7534 10234.184.5552610256.3989.89949
10264.9893.09135 10288.498.6383710314.05106.173310336.52110.421610344.01110.6979
10403.05117.511110435.95122.421110457.56122.223110471.91123.4226 10535.3125.4518
#Mann= 3 , 0 , 0
9775.603  0.0469       09775.603  0.0469       0 10535.3  0.0469       0
#XS Ineff= 2 , 0
       0                               0
Bank Sta=9775.603,10535.3
Exp/Cntr=0.3,0.1

Type RM Length L Ch R = 1 ,4788.519,149.517700,149.517700,149.517700
XS GIS Cut Line= 6
1230991.88671743613434.8998653581230900.17369303613344.616172175
1230786.88672859613155.7654475971230747.23059285 613109.82818204
1230589.29324493 612987.856098531230417.26969314612894.536452808
#Sta/Elev= 30
9730.29560.090149738.20460.79293  9764.656.845979790.99560.848839805.18355.39917
9821.719 56.5578 9830.6559.820319869.234 57.81799890.36459.436739902.65755.34772
9919.59454.569299945.32551.5174410017.6450.3887110057.5851.7535610084.3754.61888
 10097.457.2797110146.1257.9132410209.5478.9082710232.9584.2485410257.8491.64645
10277.8594.4257110293.6399.1481610304.45100.949210337.0298.5038910359.49100.7516
10367.4899.1473710378.85 99.190410409.1795.6275410457.8292.01611 10536.489.09453
#Mann= 3 , 0 , 0
9730.295  0.0429       09730.295  0.0429       0 10536.4  0.0429       0
#XS Ineff= 2 , 0
       0                               0
Bank Sta=9730.295,10536.4
Exp/Cntr=0.3,0.1

Type RM Length L Ch R = 1 ,4639.002,165.980700,165.980700,165.980700
XS GIS Cut Line= 3
1231078.69516721613268.6576157961230864.49362123613059.723320901
 1230573.0390586612933.309293762
#Sta/Elev= 30
9801.93753.779939862.69651.991899871.86255.014619876.44555.577769930.99950.87911
9935.69849.011369940.60945.619939945.19244.234949958.94152.366979963.52453.20442
9973.28748.7832810010.88 47.1722 10023.148.6228710048.4748.7341110073.5250.33904
10096.4353.9217910115.3555.6729110133.2355.03471 10183.357.4811310204.7657.29887
10208.33 57.945310229.7970.64878 10244.177.1949810287.0186.9438710304.8988.36903
10313.7690.6686910322.7791.6145310358.5391.4422710379.99 92.968510418.8591.17783
#Mann= 3 , 0 , 0
9801.937  0.0485       09801.937  0.0485       010418.85  0.0485       0
#XS Ineff= 2 , 0
       09962.104                       0
Bank Sta=9801.937,10418.85
Exp/Cntr=0.3,0.1

Type RM Length L Ch R = 1 ,4473.021,93.620700,93.620700,93.620700
XS GIS Cut Line= 3
1231210.37644547613028.119814113 1230880.2953746613012.318060741
1230550.21430373 612882.39253284
#Sta/Elev= 30
9830.54654.440579844.97754.624149864.68456.074629887.67754.817829910.66955.01638
9927.092 54.31719956.653  50.9959963.22251.083089973.07649.142739996.06838.27611
9999.35337.9299210015.7839.0275710042.0545.2614710058.4847.7600410071.6148.25284
10084.7550.4252810114.3149.6285610137.3150.3623410174.3553.7129410223.7152.92735
 10262.554.0865510273.0756.92378 10290.769.0783210301.2873.9958210316.2977.05845
10350.6481.74873 10385.987.5844210421.1684.35234 10495.283.0098710515.7480.63487
#Mann= 3 , 0 , 0
9830.546  0.0405       09830.546  0.0405       010515.74  0.0405       0
#XS Ineff= 2 , 0
       0                               0
Bank Sta=9830.546,10515.74
Exp/Cntr=0.3,0.1

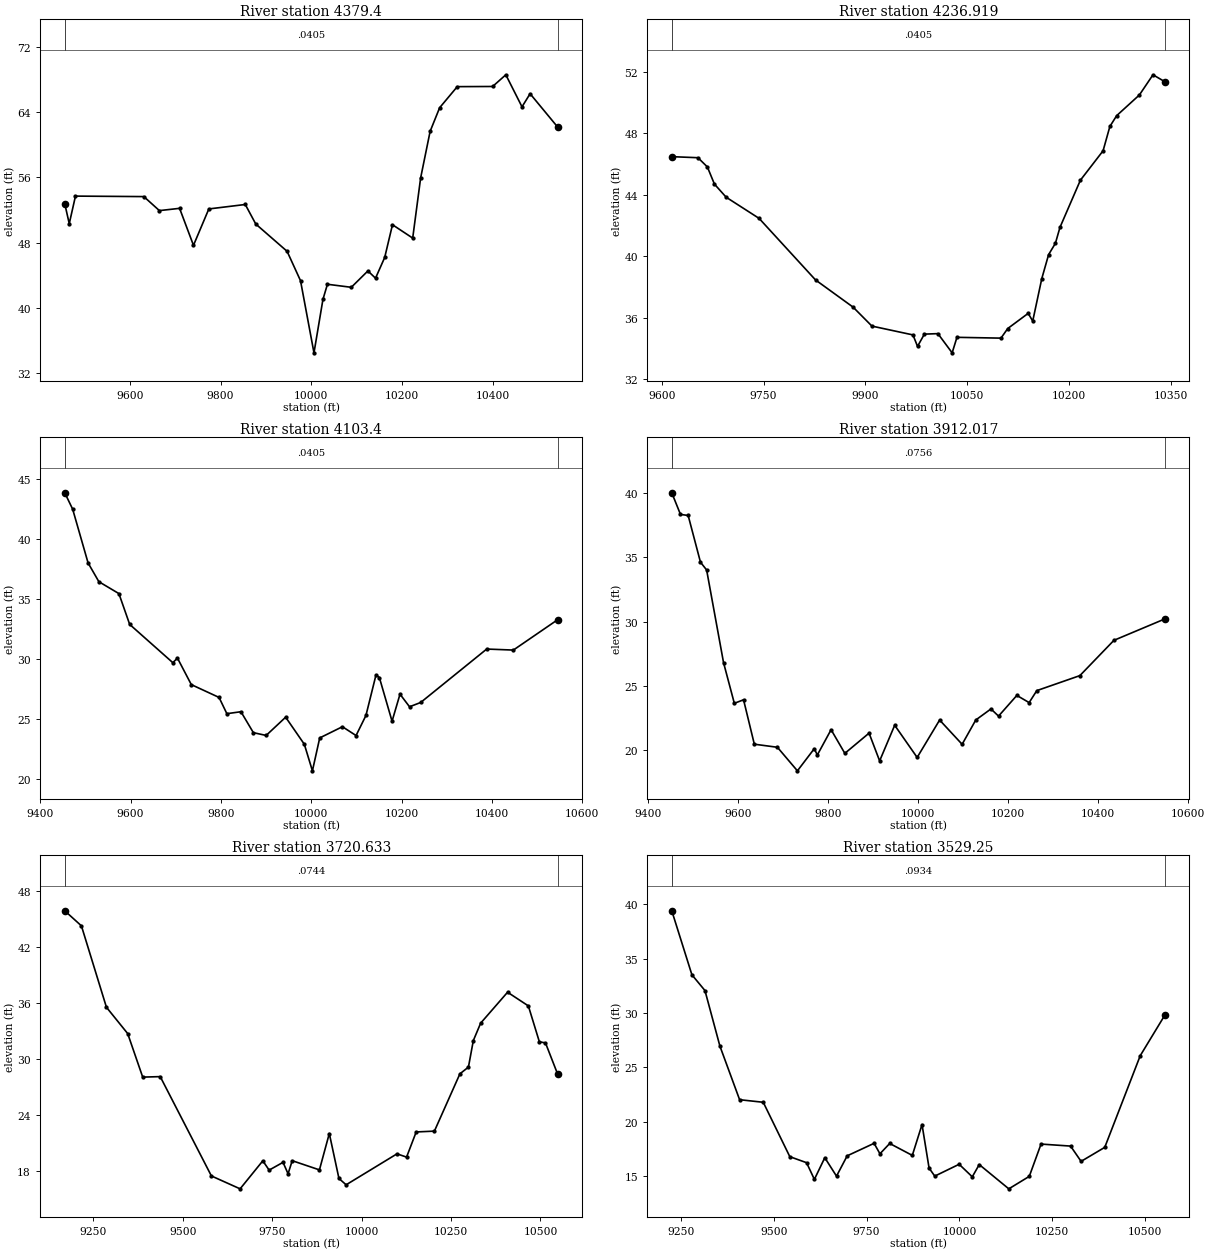
Type RM Length L Ch R = 1 ,  4379.4,142.481200,142.481200,142.481200
XS GIS Cut Line= 6
1231559.78945651613033.1838805271231189.66873013612929.263133342
1231101.30219297612921.5207237091230965.29285333612931.147718832
 1230879.6648374 612916.686557141230516.59485924612774.232832531
#Sta/Elev= 30
9456.37152.789019466.29250.346559480.00253.719539630.80553.659119665.07951.94362
9709.635 52.22149740.27747.693569774.14352.148289854.514 52.69279877.67350.29925
 9946.7246.961329976.34443.3623510006.0334.5291410025.8141.07655 10035.742.92493
10088.3542.5533710124.9844.5588510141.7643.6661710162.06 46.215910179.1550.21476
10223.76 48.578210241.2255.9318510262.1961.6491310283.1564.5384810322.0567.12136
10400.0567.1414810429.1368.5744610464.82  64.65110482.6766.25459 10543.662.16347
#Mann= 3 , 0 , 0
9456.371  0.0405       09456.371  0.0405       0 10543.6  0.0405       0
#XS Ineff= 2 , 0
       0                               0
Bank Sta=9456.371,10543.6
Exp/Cntr=0.3,0.1

Type RM Length L Ch R = 1 ,4236.919,133.518800,133.518800,133.518800
XS GIS Cut Line= 6
1231367.00298187612905.7565782371231088.74450457612812.154518023
1230983.81704322612789.4674993461230944.11476058612773.397527784
1230898.74072322612764.8898957971230667.14407429612720.461150885
#Sta/Elev= 30
9614.83146.469159653.36946.400429667.21545.800959677.59944.684419694.907  43.829
9743.36742.452979826.443 38.44689881.82736.674259909.48535.443019969.90534.86913
9976.61834.122969986.68834.9204110006.6134.9528210027.5833.7029410034.6634.71251
10099.4434.6598810109.4635.2865910139.5236.2717710146.2135.7707310159.57 38.5376
10169.5940.0958310179.6140.8328710186.2941.8654510216.3644.9351710249.7746.85066
10259.7948.4362610269.81 49.138410303.2250.4833410323.2651.7975110340.5851.34964
#Mann= 3 , 0 , 0
9614.831  0.0405       09614.831  0.0405       010340.58  0.0405       0
#XS Ineff= 2 , 0
       09876.617        10060.84       0
Bank Sta=9614.831,10340.58
Exp/Cntr=0.3,0.1

Type RM Length L Ch R = 1 ,  4103.4,191.383600,191.383600,191.383600
XS GIS Cut Line= 6
1231586.84959376612857.0347874631231175.17976324612736.630590898
1231118.94495381612711.3760816371230997.01558022612638.921050785
 1230928.8334504612605.704899845 1230568.3441215612477.169588462
#Sta/Elev= 30
9454.44843.834239471.98642.467949506.08937.99783 9529.9636.437069574.29335.44844
9598.16532.884949693.65129.701289703.88230.083129734.57427.876499795.97126.81053
 9813.2325.458189844.42225.62144 9871.9123.87996  9900.223.648279943.35825.16555
9984.72922.91343 10002.620.7039810018.7723.4420310069.0124.37361 10099.223.64014
 10121.125.3119510143.2928.6772210150.7928.4665110178.88 24.830910196.4627.08097
10217.5626.0331310242.1826.3895410388.3730.8347410447.3530.7498110545.55 33.2794
#Mann= 3 , 0 , 0
9454.448  0.0405       09454.448  0.0405       010545.55  0.0405       0
#XS Ineff= 2 , 0
       0 9858.73        10112.73       0
Bank Sta=9454.448,10545.55
Exp/Cntr=0.3,0.1

Type RM Length L Ch R = 1 ,3912.017,191.383500,191.383500,191.383500
XS GIS Cut Line= 6
1231663.96058548612643.5600761311231286.35546594612534.865524781
1231199.76664439612515.9975050791231039.37051834612488.117550213
1230937.25267218612463.8053779921230605.84330203612363.387062248
#Sta/Elev= 30
9452.16140.02057 9471.4738.339669488.56938.255889515.927 34.62429529.60634.02099
9567.22426.812499591.16223.654469611.68123.927939635.61920.475559686.91620.23618
9731.37318.40448 9768.8720.127289775.66419.637179806.23421.603689836.80519.76379
9890.62521.33526 9914.1319.177189947.58621.947749997.51419.4455210047.4722.35447
10097.4620.4671910127.8122.3568510161.5423.21687 10178.422.6586910219.0824.26698
 10246.423.7090510263.47 24.641110359.1825.8070410434.8228.5490710547.8330.21064
#Mann= 3 , 0 , 0
9452.161  0.0756       09452.161  0.0756       010547.83  0.0756       0
#XS Ineff= 2 , 0
       09836.869        10086.43       0
Bank Sta=9452.161,10547.83
Exp/Cntr=0.3,0.1

Type RM Length L Ch R = 1 ,3720.633,191.383600,191.383600,191.383600
XS GIS Cut Line= 6
1231928.63684165612587.6475624291231488.33101016612426.736651644
1231241.33014044612331.0943410251231196.07051468612320.460439697
 1230997.8171221612291.2840753941230615.21953663612182.145264462
#Sta/Elev= 30
9169.77545.880979216.37344.263789286.34135.525399345.81432.697749387.79528.02592
9436.77328.07876 9579.9217.415519660.16616.032929723.71919.042189741.37318.04191
9780.21118.878289794.334 17.64889805.93219.054439882.03318.06691 9909.6521.97274
9936.61117.14568 9956.6916.4662210098.9219.7900410125.7519.4389110152.6422.13952
10203.5922.2284110274.9228.3797510298.7429.0998310312.4231.9458510332.9533.81893
 10408.237.1379110466.3535.6687810497.1331.8155310514.2331.6984210548.4728.32417
#Mann= 3 , 0 , 0
9169.775  0.0744       09169.775  0.0744       010548.47  0.0744       0
#XS Ineff= 2 , 0
       09772.009                       0
Bank Sta=9169.775,10548.47
Exp/Cntr=0.3,0.1

Type RM Length L Ch R = 1 , 3529.25,382.767200,382.767200,382.767200
XS GIS Cut Line= 6
1231913.27583945612526.2035535421231368.55497947612295.851871863
1231198.65359792612099.7024518551231091.89692014612036.411072105
1231010.41783854612010.032598421 1230767.3450734612108.384293005
#Sta/Elev= 30
9225.44339.395839279.63633.507189314.784 32.05579355.01526.947539408.06422.01635
9471.72321.779679543.24916.775929588.34516.222099609.37914.686239637.42516.68093
9668.97614.984819697.71416.853779770.15118.004319785.90517.041499812.22417.98981
9873.03916.892739899.22419.73012  9918.215.726719933.49914.987289999.17916.07659
10034.5214.9229710053.2816.0499110132.89 13.816810187.9914.9640310219.6517.93463
10299.1917.74982 10327.516.3429610391.2117.6335310486.7726.0678210552.7529.78339
#Mann= 3 , 0 , 0
9225.443  0.0934       09225.443  0.0934       010552.75  0.0934       0
#XS Ineff= 2 , 0
       09791.017        10279.95       0
Bank Sta=9225.443,10552.75
Exp/Cntr=0.3,0.1

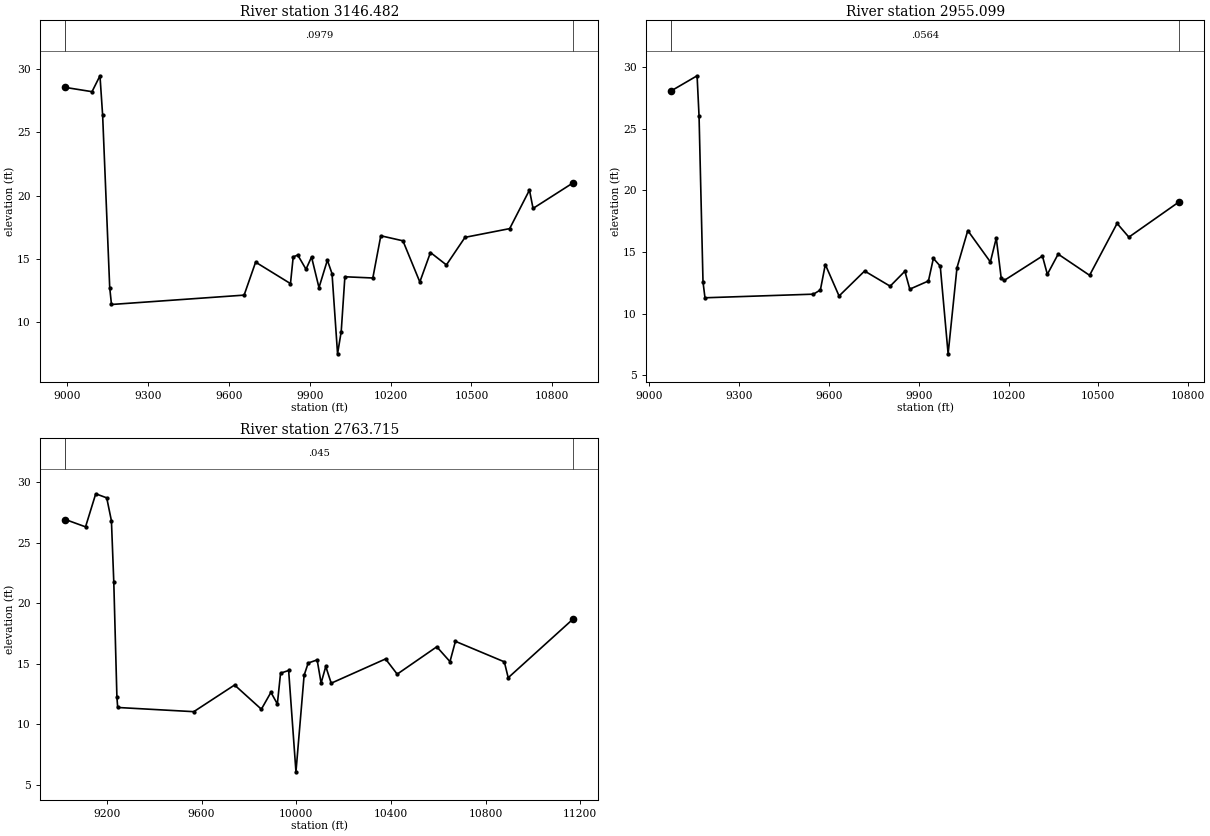
Type RM Length L Ch R = 1 ,3146.482,191.383500,191.383500,191.383500
XS GIS Cut Line= 6
 1232281.9398928611828.8140525071231582.13065818611805.281458408
1231181.01588827611899.1319238541230989.13961601611892.983887732
1230740.44017717611912.1385910061230417.11422271611973.207473427
#Sta/Elev= 30
8992.51228.555659091.07428.220729120.63629.47582 9130.4926.360819156.76812.76032
9163.33711.421829655.91412.160979698.64414.763769828.07913.070249838.19915.17754
9855.06515.327269885.74614.203759906.28815.172499933.97212.752449965.11614.91779
9982.41913.8529110002.947.52586810016.54 9.2888110030.1413.6103210133.91 13.5131
10163.51 16.845910245.72 16.447810308.4413.1997410347.9315.5248710407.1614.54538
10476.2616.7222310642.1417.41088 10715.620.4542110728.9519.0052810877.1821.01824
#Mann= 3 , 0 , 0
8992.512  0.0979       08992.512  0.0979       010877.18  0.0979       0
#XS Ineff= 2 , 0
       09714.275        10233.06       0
Bank Sta=8992.512,10877.18
Exp/Cntr=0.3,0.1

Type RM Length L Ch R = 1 ,2955.099,191.383600,191.383600,191.383600
XS GIS Cut Line= 6
1232180.55727813611730.5036382531231681.10797718611683.367015466
1231554.21712011611679.5226233151231202.01938474611688.018937409
1231106.57272744611684.730625153 1230487.7748329611696.709433347
#Sta/Elev= 30
9073.51928.062859159.54729.279349166.13825.982179179.31912.56867 9185.9111.28844
9548.40611.581879571.47311.92524  9587.913.983999633.85311.434249719.18613.45768
 9804.4912.228089853.70413.437829870.10811.986669932.47112.651429948.89714.47891
9971.89313.852129998.173 6.7453810027.7413.7172910063.8616.7358510139.3614.19224
10159.0616.1243310175.4612.8942310185.3112.6892810313.2814.6705410329.69 13.1903
10365.7914.8259210470.7913.1097310562.6717.3131310602.0516.2025510768.9319.04701
#Mann= 3 , 0 , 0
9073.519  0.0564       09073.519  0.0564       010768.93  0.0564       0
#XS Ineff= 2 , 0
       09653.728        10137.54       0
Bank Sta=9073.519,10768.93
Exp/Cntr=0.3,0.1

Type RM Length L Ch R = 1 ,2763.715,191.383600,191.383600,191.383600
XS GIS Cut Line= 6
1232254.29008883611659.8430280241231474.55617163 611546.12626949
1231416.68477011611534.5172662591231341.07161632611514.816482469
1231202.13599163611470.794723779 1230128.3273809611481.655402213
#Sta/Elev= 30
9024.81426.925949109.60726.322799152.70129.05659 9199.1128.720699218.99926.82165
9228.944  21.7799242.20412.223869245.51911.388199567.06611.041459739.465  13.246
9852.674 11.24469893.10612.640139920.22911.67892 9933.7914.222259967.93314.44772
9998.8576.066966 10033.314.0455610050.5215.0631510088.4115.3221310105.1613.40521
10124.85 14.781910147.8213.3952410377.4915.40146 10426.714.1442610594.03 16.4056
10649.81 15.179310672.7816.8575510879.4815.1622510895.8813.8478311169.5718.69192
#Mann= 3 , 0 , 0
9024.814   0.045       09024.814   0.045       011169.57   0.045       0
#XS Ineff= 2 , 0
       09646.705        10114.47       0
Bank Sta=9024.814,11169.57
Exp/Cntr=0.3,0.1