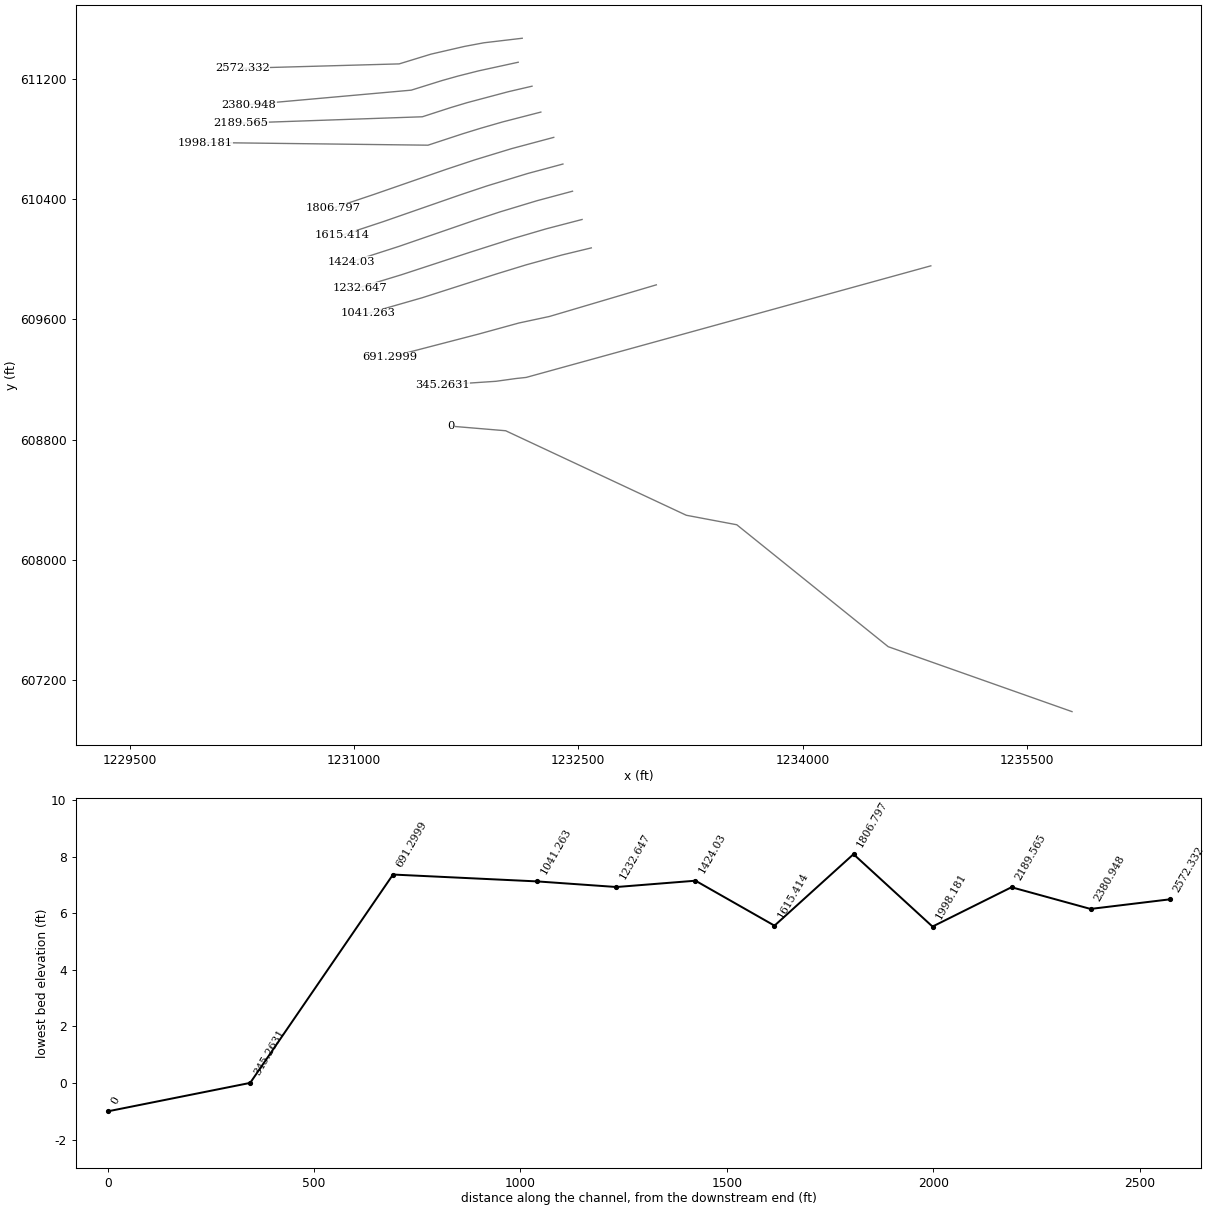
HEC-RAS study 301_ras.prj: 301

--- 301_ras.g01 (geometry) --- (continued)

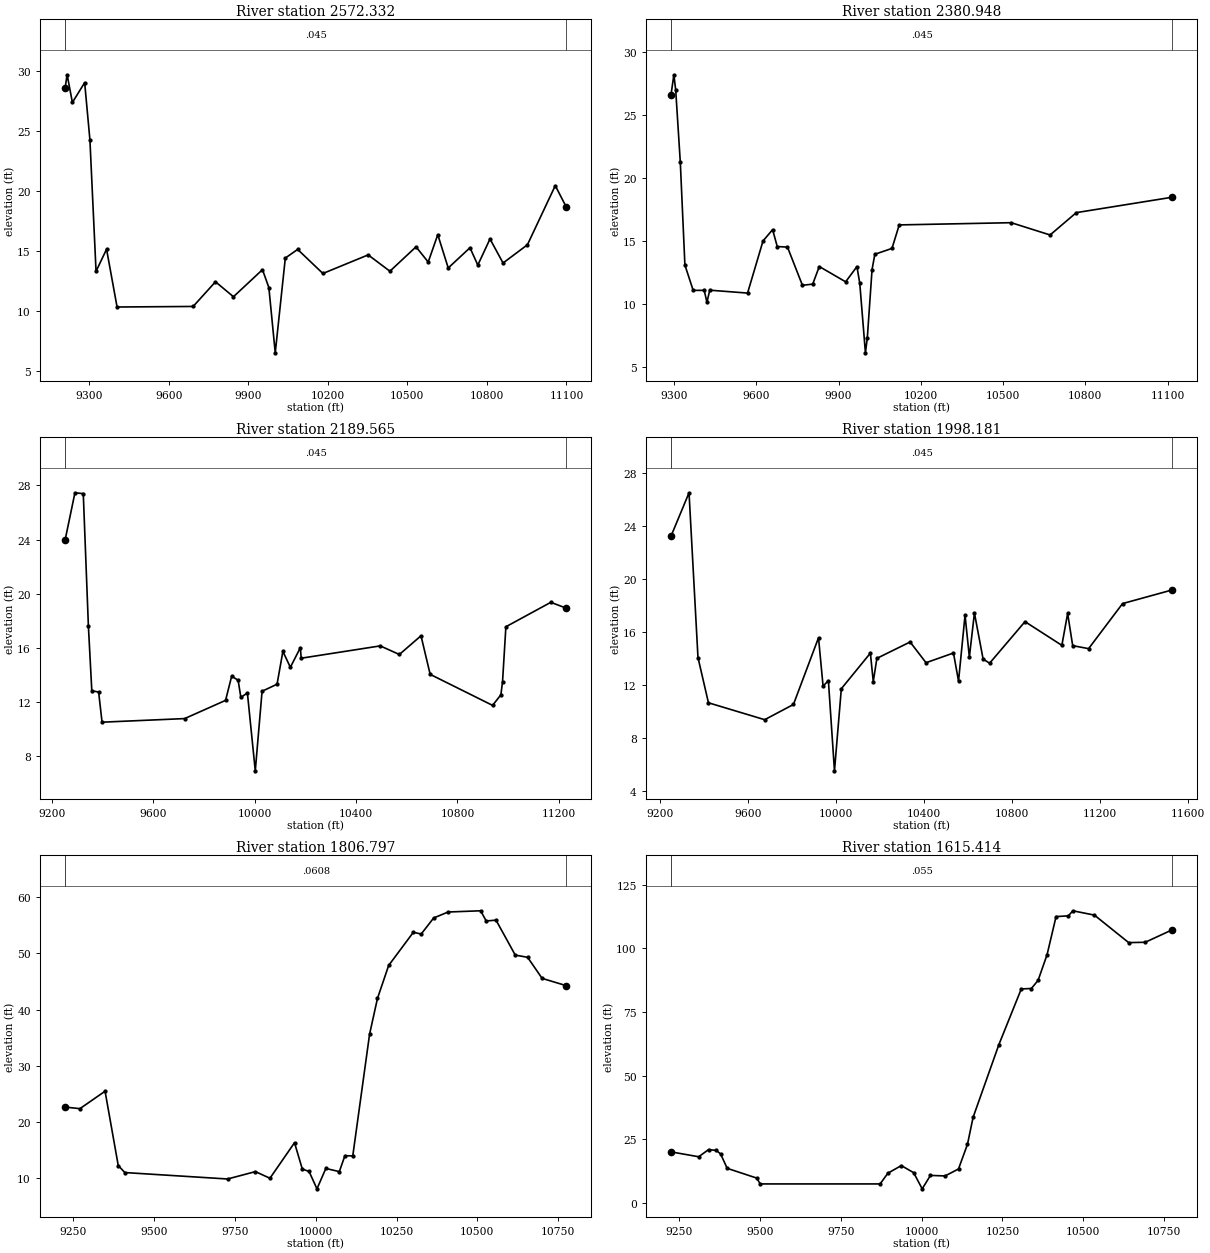
Type RM Length L Ch R = 1 ,2572.332,191.383600,191.383600,191.383600
XS GIS Cut Line= 6
 1232125.2576701611472.4388008861231868.84761828611442.237123773
 1231739.0951589   611418.0394621231515.09209234611366.572540879
1231302.48892269611301.6815058891230254.97123277611272.577845335
#Sta/Elev= 30
9209.67228.614459217.10529.685229236.92627.375359283.175 29.02829302.99624.25875
9326.12113.288559365.76315.130849405.40510.310439692.25110.356349776.52312.41476
9844.32211.167369953.727 13.42549977.79211.9325410001.89 6.4866110039.84 14.3945
10086.3915.1159510181.57 13.106310352.2414.6578710434.2913.2957710532.75 15.3314
 10578.714.06121 10614.816.3466410654.1913.5672910736.24 15.254510765.7813.80822
10811.7315.9880110860.96 13.979910952.8615.5020611057.8920.4378711099.9518.62433
#Mann= 3 , 0 , 0
9209.672   0.045       09209.672   0.045       011099.95   0.045       0
#XS Ineff= 2 , 0
       09672.499        10119.75       0
Bank Sta=9209.672,11099.95
Exp/Cntr=0.3,0.1

Type RM Length L Ch R = 1 ,2380.948,191.383500,191.383500,191.383500
XS GIS Cut Line= 6
1232098.43414772611312.6703660941231833.98603982611255.334055871
1231698.99307397611221.4423061011231589.49158648611190.884116948
1231383.34429908611126.7604709271230299.30767909 611030.03140378
#Sta/Elev= 30
9289.31826.597779299.61728.160059306.31926.939229323.07121.229839339.82413.10199
9369.979 11.09249410.18611.095679420.258 10.14989430.34711.108729568.27510.87935
9624.66715.005919659.60715.90206 9676.5214.562939713.83114.51991 9768.3311.49698
9805.79811.587679829.77912.982939925.92811.771039967.135  12.9769977.43711.64693
9998.0416.14896610004.937.33272510022.1812.7356610032.3513.9507210094.9314.41766
10121.2816.2756910529.7216.4509510671.3615.4785610766.8817.2468611117.0218.46846
#Mann= 3 , 0 , 0
9289.318   0.045       09289.318   0.045       011117.02   0.045       0
#XS Ineff= 2 , 0
       09699.022        10120.41       0
Bank Sta=9289.318,11117.02
Exp/Cntr=0.3,0.1

Type RM Length L Ch R = 1 ,2189.565,191.383600,191.383600,191.383600
XS GIS Cut Line= 6
1232190.74731126611153.115281597  1232032.851944611116.562138453
1231757.82945672611043.7242300811231648.89186215611011.208746657
1231457.47494254 610949.47297886 1230241.9987973610907.153918982
#Sta/Elev= 30
9252.507 23.98479291.04527.452279323.93827.388899344.14317.606359357.61412.83096
9384.55512.732979398.02510.508529723.94810.774669885.343 12.12029909.467 13.9123
9934.90513.60096 9945.6212.344359971.50112.6625710002.536.91530910029.3712.79272
10088.4613.3141510111.44 15.735610140.9914.5642910180.3816.0094810183.6715.23354
10495.5316.1437310571.0415.5088910656.3916.89071 10692.514.0416210938.7111.75068
10971.5412.5299210978.1113.5104910991.2417.5559411168.5119.3614711230.1318.92482
#Mann= 3 , 0 , 0
9252.507   0.045       09252.507   0.045       011230.13   0.045       0
#XS Ineff= 2 , 0
       09753.112        10124.16       0
Bank Sta=9252.507,11230.13
Exp/Cntr=0.3,0.1

Type RM Length L Ch R = 1 ,1998.181,191.383600,191.383600,191.383600
XS GIS Cut Line= 6
1232249.66673967610980.7445162391231993.62016734610915.000317529
1231846.45547518610872.7752746641231726.90033153610836.094393402
1231495.31300101610760.2879896911230005.43936309610778.121500283
#Sta/Elev= 30
9251.64223.218439333.29226.47872 9373.9114.064789421.41810.65433  9676.99.380074
9807.37910.527769921.24915.554439941.95311.911269966.10712.324539993.7125.526325
10024.8411.7137110156.7614.3973410169.8812.2514410186.2914.0024610337.2115.23609
 10409.413.6730310534.0814.4051610557.0512.2910910586.5817.2499210606.2614.10042
10629.2317.42054 10668.613.9498110698.1313.63503 10858.916.7688411026.2414.98204
11052.4917.3867111075.4614.9597111147.6414.7339511301.8518.1293511527.8219.16015
#Mann= 3 , 0 , 0
9251.642   0.045       09251.642   0.045       011527.82   0.045       0
#XS Ineff= 2 , 0
       09858.101        10126.93       0
Bank Sta=9251.642,11527.82
Exp/Cntr=0.3,0.1

Type RM Length L Ch R = 1 ,1806.797,191.383600,191.383600,191.383600
XS GIS Cut Line= 6
1232335.92027597610812.3048311131232054.15615209610737.292880226
1231807.61184039610662.4024422161231619.95865932610600.366898298
1231135.41005762610432.8717702151230858.86134067610340.424230336
#Sta/Elev= 30
9224.41222.642959269.98922.358729347.86825.461189388.66212.235179409.07910.98205
9727.0499.8361439813.17911.14819  9858.19.967388 9934.1216.296159958.30811.59238
9979.064 11.189510003.57 8.08221 10031.1  11.71410072.7611.1480310090.1213.97941
10114.4213.94749 10166.535.64315 10190.841.9835810225.5147.8633810301.8953.76479
10326.1953.4553610364.7856.3162810409.5157.37528 10510.157.5945610527.3955.77621
10557.6755.9279710617.3449.6981810655.3949.3129110700.3645.5594610775.5944.25004
#Mann= 3 , 0 , 0
9224.412  0.0608       09224.412  0.0608       010775.59  0.0608       0
#XS Ineff= 2 , 0
       09927.666                       0
Bank Sta=9224.412,10775.59
Exp/Cntr=0.3,0.1

Type RM Length L Ch R = 1 ,1615.414,191.383500,191.383500,191.383500
XS GIS Cut Line= 6
1232397.31096689610634.7694783111232161.81643509610571.681500801
1231890.62704946610489.2802448261231706.65478549610427.990542678
1231197.41374502610251.5516565591230919.95947505610160.205195633
#Sta/Elev= 30
9223.905 20.07459309.40218.154989339.971 20.95599363.747 20.66039377.33319.26226
9397.71213.612989489.5659.7672519499.8237.4868779871.2627.4868779895.46811.71701
9936.96614.68535 9975.1211.9064210001.585.558507 10027.210.8321910072.3410.62182
10114.0113.3579110141.8523.0846110159.1433.6134510239.0162.1789610308.4584.05327
 10339.784.2187610360.5487.4406410388.3197.5195910416.09112.447410454.29 112.759
10468.18114.7411 10534.9113.036410640.96102.237910692.27102.3769 10776.1107.2858
#Mann= 3 , 0 , 0
9223.905   0.055       09223.905   0.055       0 10776.1   0.055       0
#XS Ineff= 2 , 0
       09931.312                       0
Bank Sta=9223.905,10776.1
Exp/Cntr=0.3,0.1

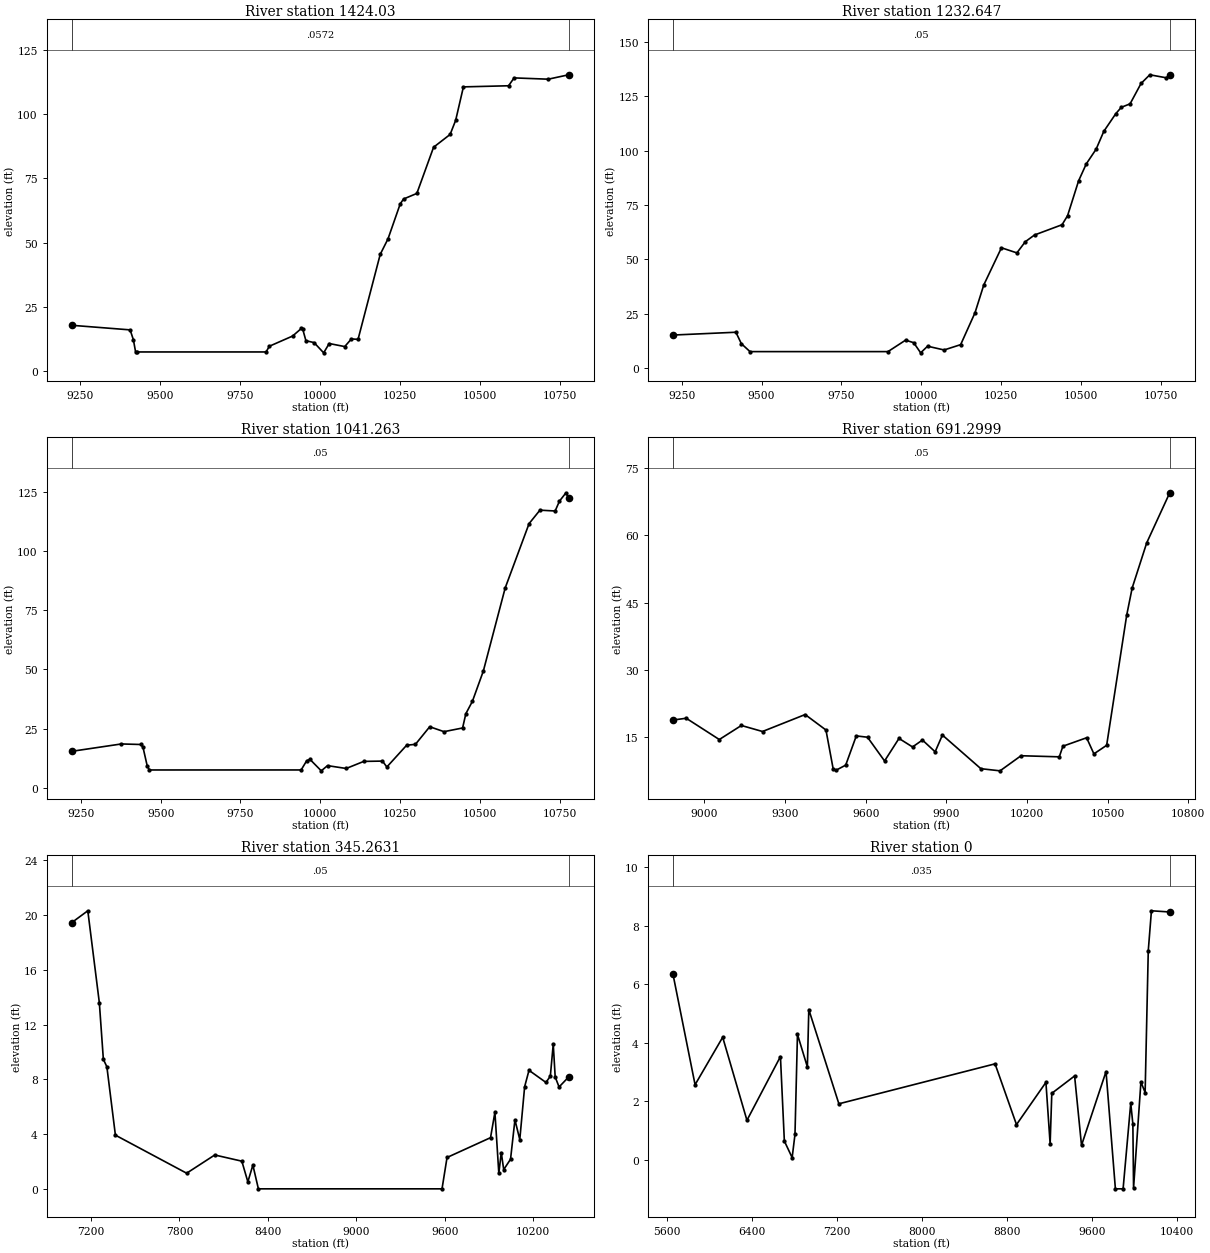
Type RM Length L Ch R = 1 , 1424.03,191.383600,191.383600,191.383600
XS GIS Cut Line= 6
1232461.35502603610453.7467822661232224.91523939610390.682834732
1231977.31935363610316.1722549741231809.10331571610260.851625644
1231301.60085519610086.4054878091230980.87670926 609983.49139617
#Sta/Elev= 30
9223.08417.855619405.39916.074249415.58512.245289422.3767.6008229425.7727.486877
9830.5197.492401 9840.889.7167079913.45713.673989941.22216.668919944.69316.57273
9955.10511.876979980.75611.1182710010.637.14578710027.9810.7679510076.549.578123
10097.36   12.5610118.1712.3835410187.5545.4493310211.8351.4586210249.9965.05647
10260.3966.9647410302.0269.1371210354.3987.1052510406.0992.0767810423.4397.56215
10447.66110.575710588.93111.008810606.16114.068410712.98113.569210776.92115.2815
#Mann= 3 , 0 , 0
9223.084  0.0572       09223.084  0.0572       010776.92  0.0572       0
#XS Ineff= 2 , 0
       09937.127                       0
Bank Sta=9223.084,10776.92
Exp/Cntr=0.3,0.1

Type RM Length L Ch R = 1 ,1232.647,191.383600,191.383600,191.383600
XS GIS Cut Line= 6
1232525.41517184610265.4481591971232285.72751642 610203.25318286
1232065.37454439610138.9228212521231774.71863502610046.638828507
1231318.82262186609897.7314438651231037.75329647609812.380295657
#Sta/Elev= 30
9222.26915.110279419.59916.406079436.54611.151169463.6627.4868779895.639 7.48741
9950.71312.760269976.23111.59064 9997.926.92303610019.619.97558610071.388.241633
10123.1510.6929210168.0225.3495510195.63 38.213310250.8555.2879310299.1752.93543
10325.5758.0846810354.3961.1773110440.6865.9043110457.9370.0929610492.3986.11639
10516.3993.9022910547.25 100.68410571.25108.878810608.97117.056610626.11  119.96
10653.54121.548710687.83130.919910715.26134.932210766.69133.547510777.74134.9005
#Mann= 3 , 0 , 0
9222.269    0.05       09222.269    0.05       010777.74    0.05       0
#XS Ineff= 2 , 0
       09943.967                       0
Bank Sta=9222.269,10777.74
Exp/Cntr=0.3,0.1

Type RM Length L Ch R = 1 ,1041.263,349.963200,349.963200,349.963200
XS GIS Cut Line= 6
1232587.01554417610076.2237033781232391.39000618610029.134702777
1232151.95742986609963.4597914221231959.81654363609904.891740882
1231456.47662795609744.2296104191231092.67895973609640.213344125
#Sta/Elev= 30
9221.44315.370039376.65218.477639437.484 18.25049444.27517.200469457.8559.127754
9464.6467.4868779940.0887.496349 9957.3111.351169967.64311.9831210003.177.120338
10022.759.32149110081.298.11869410136.39 11.108910194.9411.2403610208.718.747849
 10270.717.9412110298.2518.3175810343.0225.7508910387.7923.6691110446.0325.22661
 10456.331.2767910476.8236.4969110511.0449.2707110579.4684.3481810654.38111.5569
10688.42117.239110736.08  116.8910749.69121.074510770.12124.584210778.56122.2563
#Mann= 3 , 0 , 0
9221.443    0.05       09221.443    0.05       010778.56    0.05       0
#XS Ineff= 2 , 0
       09948.361                       0
Bank Sta=9221.443,10778.56
Exp/Cntr=0.3,0.1

Type RM Length L Ch R = 1 ,691.2999,346.036800,346.036800,346.036800
XS GIS Cut Line= 5
1233021.73769087609830.159751698 1232307.9465034609619.741707996
1232103.10626316609576.0117690861231833.82190242609502.361345619
1231237.71378756609348.155771494
#Sta/Elev= 30
8882.77618.722588932.36419.126189055.49914.366229137.58917.508659216.25816.16152
9374.87419.952029452.26716.492849479.3017.7385519489.8927.4996889525.7128.642693
9565.14115.176769606.93314.881019670.3259.5703699724.00114.610929774.32212.70626
9811.22514.248599858.49411.620929885.47915.3656410028.567.84404710099.997.363431
10177.9910.7417710320.3210.4959710333.8812.8748710421.9814.76076 10449.111.15665
10496.5413.0767910571.0942.1682210591.4348.2491810645.6558.36436 10731.369.55113
#Mann= 3 , 0 , 0
8882.776    0.05       08882.776    0.05       0 10731.3    0.05       0
#XS Ineff= 2 , 0
       09957.989                       0
Bank Sta=8882.776,10731.3
Exp/Cntr=0.3,0.1

Type RM Length L Ch R = 1 ,345.2631,345.263100,345.263100,345.263100
XS GIS Cut Line= 6
1234856.89723906609956.7224791651232151.59783688 609213.55548133
1232082.70726168609206.1789632441231949.41672662609187.745923594
1231699.06003141609171.0516607461231590.22704718 609162.17107664
#Sta/Elev= 30
7070.59319.443577178.97720.302787257.23213.587667284.451 9.458917308.2678.915589
7366.1083.9258797849.2451.1468628039.7782.4782928223.5062.0258288264.3350.515695
8298.3581.7402618335.7850.0065629581.0540.0065629615.078 2.295199910.0283.741609
9939.7245.5954969966.2221.142106  9982.82.6534479999.3791.40971910045.722.170032
 10075.55.04360710108.41 3.6019910141.297.46077210170.898.65787610285.977.771498
10315.578.234021 10335.310.5703210348.478.171564 10374.87.44356410440.078.173973
#Mann= 3 , 0 , 0
7070.593    0.05       07070.593    0.05       010440.07    0.05       0
#XS Ineff= 2 , 0
       09940.602                       0
Bank Sta=7070.593,10440.07
Exp/Cntr=0.3,0.1

Type RM Length L Ch R = 1 ,       0,0.000000,0.000000,0.000000
XS GIS Cut Line= 6
1235800.84424806606987.7718308271234572.13110223607420.194482982
1233559.62928259608232.3053175211233222.12867606608295.586681262
1232014.47729528608858.430440709 1231650.4541558608888.832802027
#Sta/Elev= 30
 5653.486.3617415862.4342.5634546122.3854.1874976350.7141.3461836666.0273.526834
6702.8630.6359236776.2250.0694616802.9020.8624176826.2444.2862786919.6143.171161
6932.952 5.135547216.1631.9104368686.2143.2776128888.1461.1981899165.1712.644027
9204.795  0.54139220.5252.2691029435.0692.8627049500.1770.4901899731.0253.012834
9819.155  -0.9999891.718  -0.9999963.6881.9331399983.5991.2210759990.198-0.96863
10059.452.65948710099.032.29470410128.717.15308210158.388.51447510330.898.473576
#Mann= 3 , 0 , 0
 5653.48   0.035       0 5653.48   0.035       010330.89   0.035       0
#XS Ineff= 2 , 0
       09903.975                       0
Bank Sta=5653.48,10330.89
Exp/Cntr=0.3,0.1